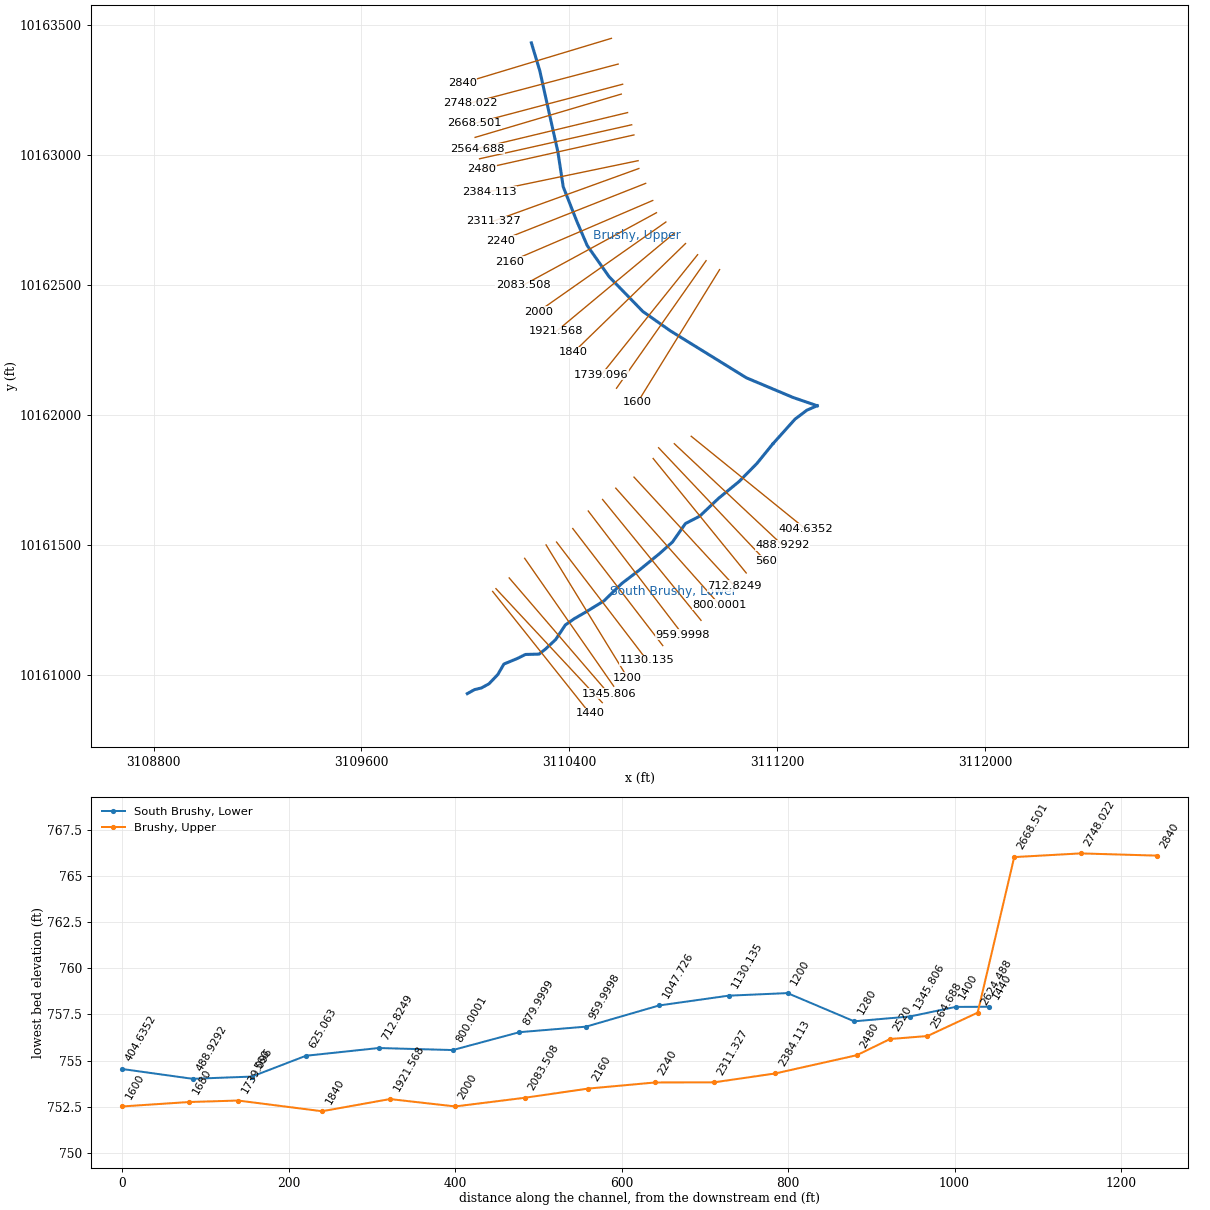
--- UB100yr2.prj (project) ---

Proj Title=Upper Brushy - 2nd run
Current Plan=p02
Default Exp/Contr=0.3,0.1
English Units
Geom File=g01
Flow File=f01
Flow File=f02
Plan File=p01
Plan File=p02
Y Axis Title=Elevation
X Axis Title(PF)=Main Channel Distance
X Axis Title(XS)=Station
BEGIN DESCRIPTION:
END DESCRIPTION:
DSS Export Rating Curves= 0
DSS Export Rating Curve Sorted= 0
DSS Export Volume Flow Curves= 0
DXF OffsetX= 0
DXF OffsetY= 0
DXF ScaleX= 1
DXF ScaleY= 10

--- UB100yr2.p02 (plan) ---

Plan Title=Hermine with dams
Program Version=4.10
Short Identifier=HermineDams
Geom File=g01
Flow File=f02
Subcritical Flow
K Sum by GR= 0
Std Step Tol= 0.01
Critical Tol= 0.01
Num of Std Step Trials= 20
Max Error Tol= 0.3
Flow Tol Ratio= 0.001
Split Flow NTrial= 30
Split Flow Tol= 0.02
Split Flow Ratio= 0.02
Log Output Level= 0
Friction Slope Method= 1
Unsteady Friction Slope Method= 2
Unsteady Bridges Friction Slope Method= 1
Parabolic Critical Depth
Global Vel Dist= 15 , 15 , 15
Global Log Level= 0
CheckData=True
Encroach Param=-1 ,0,0, 0
Computation Interval=1HOUR
Output Interval=1HOUR
Run HTab= 0
Run UNet= 0
Run PostProcess= 0
Run WQNet= 0
UNET Theta= 1
UNET Theta Warmup= 1
UNET ZTol= 0.02
UNET ZSATol= 0.05
UNET MxIter= 20
UNET MaxInSteps= 0
UNET DtIC= 0
UNET DtMin= 0
UNET MaxCRTS= 20
UNET WFStab= 2
UNET SFStab= 1
UNET WFX= 1
UNET SFX= 1
UNET DSS MLevel= 4
UNET DZMax Abort= 100
UNET Convert EG Bridges= 0
UNET Use Existing IB Tables=-1
UNET Froude Reduction=False
UNET Froude Limit= 1
UNET Froude Power= 10
UNET Time Slicing=0,0, 5
UNET Junction Losses=0
Instantaneous Interval=1HOUR
Write IC File= 0
Write IC File at Sim End=0
Echo Input=False
Echo Parameters=False
Echo Output=False
Write Detailed= 0
WQ AD Non Conservative
WQ ULTIMATE=-1
WQ Max Comp Step=1HOUR
WQ Output Interval=15MIN
WQ Output Selected Increments= 0
WQ Output face flow=0
WQ Output face velocity=0
WQ Output face area=0
WQ Output face dispersion=0
WQ Output cell volume=0
WQ Output cell surface area=0
WQ Output cell continuity=0
WQ Output cumulative cell continuity=0
WQ Output face conc=0
WQ Output face dconc_dx=0
WQ Output face courant=0
WQ Output face peclet=0
WQ Output face adv mass=0
WQ Output face disp mass=0
WQ Output cell mass=0
WQ Output cell source sink temp=0
WQ Output cell source sink nsm=0
WQ Output MaxMinRange=-1
WQ Daily Max Min Mean=-1
WQ Daily Range=0
WQ Daily Time=0
WQ Create Restart=0
WQ Fixed Restart=0
WQ System Summary=0
WQ Use Fixed Temperature=0
Sorting and Armoring Iterations= 10
XS Update Threshold= 0.02
Hydraulics Update Threshold= 0.02
Energy Slope Method= 1
Volume Change Method= 0
XS Weighting Method= 0
Number of US Weighted Cross Sections= 1
Number of DS Weighted Cross Sections= 1
Upstream XS Weight=0.25
Main XS Weight=0.5
Downstream XS Weight=0.25
Number of DS XS's Weighted with US Boundary= 1
Upstream Boundary Weight= 1
Weight of XSs Associated with US Boundary= 0
Number of US XS's Weighted with DS Boundary= 1
Downstream Boundary Weight= 0.5
Weight of XSs Associated with DS Boundary= 0.5
Sediment Output Level= 4
Mass or Volume Output= 0
Output Increment Type= 1
Profile and TS Output Increment= 10
XS Output Flag= 0
XS Output Increment= 10
Disregard all LS=0
Disregard all Conn=0
Disregard all Breaches=0
Disregard all Pumps=0

--- UB100yr2.p01 (plan) ---

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Plan Title=Simplified100Adjusted
Short Identifier=Reduced
Geom File=g01
Flow File=f01

--- UB100yr2.f02 (steady flow) ---

Flow Title=Flow for Hermine and dams
Program Version=4.10
Number of Profiles= 1
Profile Names=PF 1
River Rch & RM=Brushy,Upper           ,2840
   16300
River Rch & RM=Brushy,Lower           ,945.4837
   18800
River Rch & RM=South Brushy,Lower           ,1440
    2500
Boundary for River Rch & Prof#=Brushy,Upper           , 1
Up Type= 0
Dn Type= 0
Boundary for River Rch & Prof#=Brushy,Lower           , 1
Up Type= 0
Dn Type= 3
Dn Slope=0.008
Boundary for River Rch & Prof#=South Brushy,Lower           , 1
Up Type= 0
Dn Type= 0
DSS Import GetInterval= 0
DSS Import GetPeak= 0
DSS Import FillOption= 0

--- UB100yr2.f01 (steady flow) ---

Flow Title=Flow with dams estimated
Program Version=4.10
Number of Profiles= 1
Profile Names=PF 1
River Rch & RM=Brushy,Upper           ,2840
   16000
River Rch & RM=Brushy,Lower           ,945.4837
   24000
River Rch & RM=South Brushy,Lower           ,1440
    8000
Boundary for River Rch & Prof#=South Brushy,Lower           , 1
Up Type= 0
Dn Type= 0
Boundary for River Rch & Prof#=Brushy,Lower           , 1
Up Type= 0
Dn Type= 3
Dn Slope=0.008
Boundary for River Rch & Prof#=Brushy,Upper           , 1
Up Type= 0
Dn Type= 0
DSS Import GetInterval= 0
DSS Import GetPeak= 0
DSS Import FillOption= 0

--- UB100yr2.g01 (geometry) ---

Geom Title=FewerCS
Program Version=4.10

Junct Name=2
Junct Desc=, 0 , 0 ,-1 ,0
Up River,Reach=South Brushy    ,Lower
Up River,Reach=Brushy          ,Upper
Dn River,Reach=Brushy          ,Lower
Junc L&A=404.35,0
Junc L&A=300.27,0

River Reach=South Brushy    ,Lower
Reach XY= 29
3110007.99586976 10160928.2077233110035.5132031710160943.4711439
3110062.4229262810160949.9816296 3110091.502920610160966.0406526
3110125.3568555110161001.63080453110148.7944726910161041.9952251
 3110201.311756110161063.69662533110231.6939131910161078.8878679
 3110284.211196610161080.18970253110309.81875694 10161100.589268
3110348.2199268610161136.41629613110385.3396032810161192.6028635
3110419.6279205110161216.47453493110465.2006640110161242.9502038
3110533.7769704510161285.05084133110602.3536049410161351.8912589
 3110668.759640110161402.67232533110746.0167034310161465.6065826
 3110797.231824110161511.17932613110847.5791643610161582.7940123
3110902.2667190110161611.00589813110974.7491855910161679.5822045
 3111054.1765202 10161744.6864053111122.3187723510161813.6967657
3111185.1982397710161890.96760853111184.6926633410161890.3465468
3111269.4543048410161984.70364153111315.1763262710162019.2810002
3111354.80255935 10162036.209444

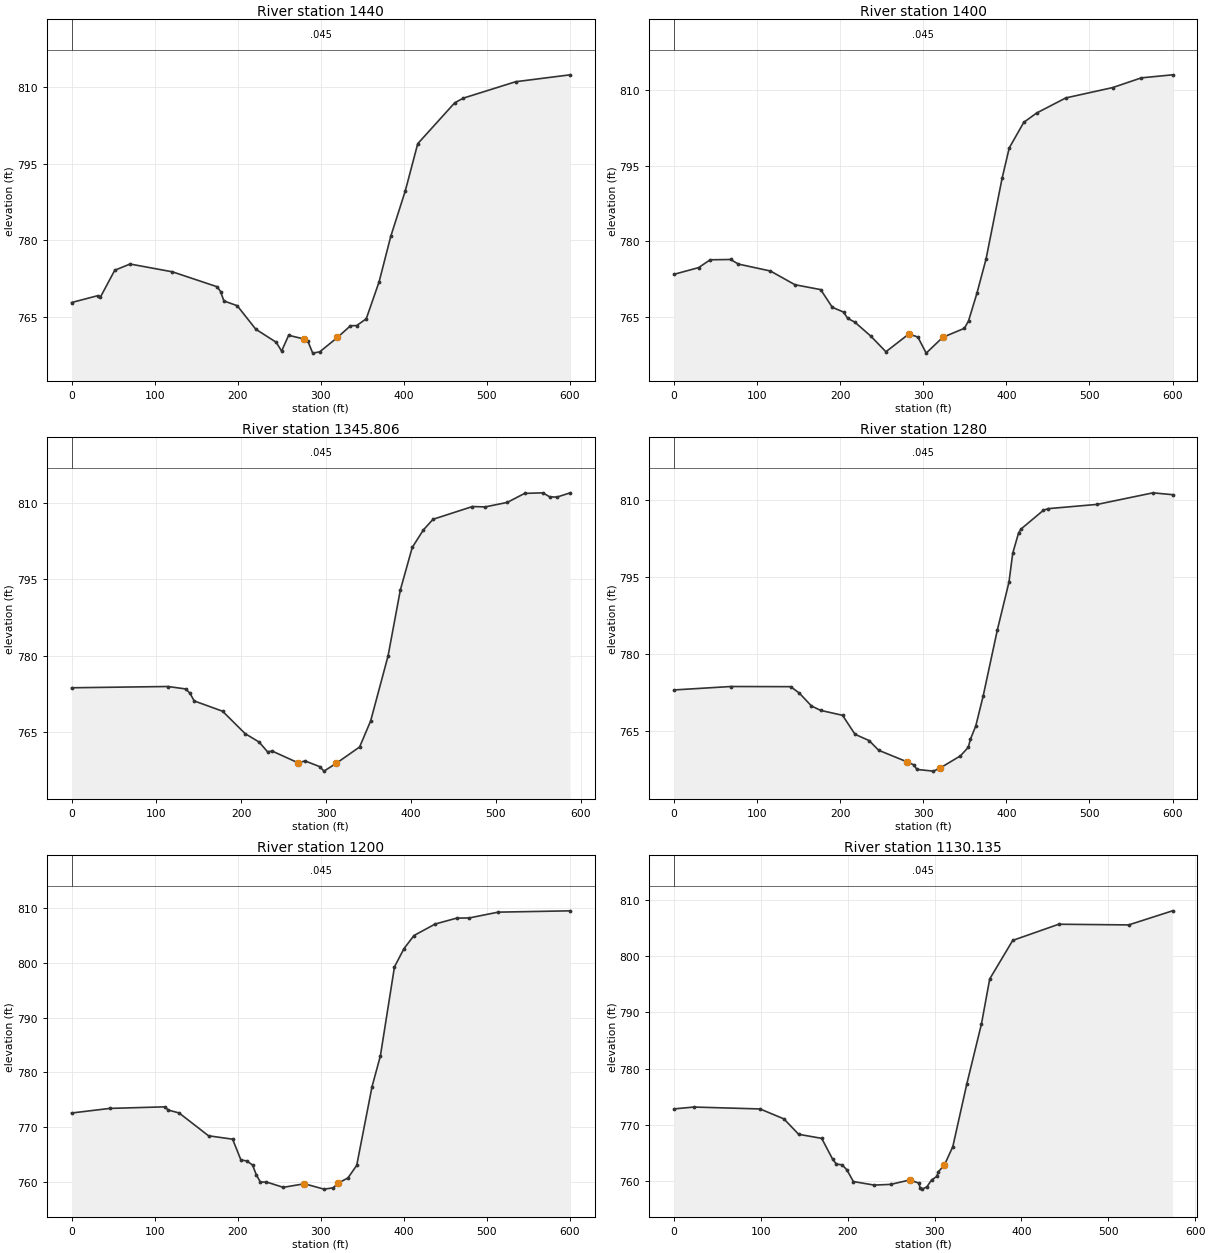
Type RM Length L Ch R = 1 ,1440    ,37.08,40.28,43.44
XS GIS Cut Line= 2
3110105.5235618710161321.39853773110479.3735359310160852.1051849
#Sta/Elev= 30
       0  767.83   31.47  769.17   34.47  768.82   51.96  774.15   70.44  775.37
   121.4  773.84  175.35  770.91  179.35  769.97  183.35  768.14  199.33  767.21
  221.82  762.59  246.29  760.05  252.79  758.32  261.28  761.41     280  760.68
  284.26  760.32  290.26  757.92  298.75  758.18     320  760.99  335.72  763.28
  343.22  763.32  354.71  764.65  370.19   771.9  384.18  780.78  401.67  789.68
  416.66  798.93  461.12  806.93  471.61  807.86  534.56  811.07     600  812.42
#Mann= 1 ,-1 , 0
       0    .045       0
Bank Sta=280,320
XS Rating Curve= 0 ,0
Exp/Cntr=0.3,0.1

Type RM Length L Ch R = 1 ,1400    ,58.34,54.87,52.52
XS GIS Cut Line= 2
3110118.1754394510161332.08289953110527.4803951110160893.3698662
#Sta/Elev= 30
       0   773.5    29.5  774.82    43.5  776.37      68  776.43    77.5  775.52
     116  774.15   145.5  771.44   176.5  770.47   190.5  766.97     204  766.03
     209  764.79   217.5  764.05     237  761.25     255  758.18  282.84  761.72
   293.5  761.08   303.5  757.91  323.39  761.03   349.5  762.82   354.5   764.3
   364.5  769.71   375.5  776.48     395  792.59   403.5  798.51     421  803.56
   436.5   805.4   471.5  808.38     528  810.43   562.5  812.35     600  812.95
#Mann= 1 ,-1 , 0
       0    .045       0
Bank Sta=282.84,323.39
XS Rating Curve= 0 ,0
Exp/Cntr=0.3,0.1

Type RM Length L Ch R = 1 ,1345.806,69.32,66.96,63.48
XS GIS Cut Line= 2
3110169.13629553 10161373.462738 3110551.948850110160928.1503084
#Sta/Elev= 30
       0  773.74  113.45  773.99  134.44  773.51  139.44  772.68  144.44  771.16
  177.92  769.14  204.41  764.75   220.9   763.1   230.9  761.18  236.39  761.32
  267.24  758.99  274.88   759.4  292.37  758.27  297.37  757.39  311.99  758.94
  339.35  762.13  352.34  767.24  372.83  779.97  387.33  792.93  401.32  801.26
  414.31  804.67  425.81  806.79  472.29  809.29  487.28  809.22  513.27   810.1
  533.76  811.87  555.25  811.98  563.25   811.2  571.75  811.14  587.24  811.97
#Mann= 1 ,-1 , 0
       0    .045       0
Bank Sta=267.24,311.99
XS Rating Curve= 0 ,0
Exp/Cntr=0.3,0.1

Type RM Length L Ch R = 1 ,1280    ,82.34,80.09,77.85
XS GIS Cut Line= 2
3110228.6453628510161449.05641893110571.46718377 10160956.640737
#Sta/Elev= 30
       0  772.97   68.44  773.64  140.38  773.61  150.87  772.34  165.36  769.85
  176.35  768.99  202.83  768.02  217.82  764.32  234.81  763.09   246.3   761.2
     280  758.97  288.76  758.34  292.26  757.46  312.24  757.13     320  757.71
  344.72  760.11  354.21  761.79  356.71  763.34   363.2  765.95  372.19  771.87
  389.18   784.7  403.17  794.02  407.66  799.63  414.66  803.58  417.66  804.37
  444.63  808.03  450.13  808.34  509.58  809.18  576.52  811.43     600  811.07
#Mann= 1 ,-1 , 0
       0    .045       0
Bank Sta=280,320
XS Rating Curve= 0 ,0
Exp/Cntr=0.3,0.1

Type RM Length L Ch R = 1 ,1200    ,66.77,70.9,75.01
XS GIS Cut Line= 2
3110311.1799746810161500.41786473110625.0966696710160989.0898191
#Sta/Elev= 30
       0  772.56   45.96   773.4  112.91  773.69   115.9  773.12  129.39  772.57
  164.86   768.4  193.84  767.78  203.83  763.99  210.83  763.81  217.82  763.07
  222.32  761.29  227.31  759.93  234.31  759.97  254.79  758.99   280.3  759.64
  303.75  758.66  314.74  758.89  320.93  759.75  332.72  760.71  343.21     763
   361.7   777.4  371.69  782.97  388.68  799.26  400.17  802.59  412.16  804.97
  437.64  807.07  463.61  808.15   478.6  808.18  513.57  809.24     600  809.48
#Mann= 1 ,-1 , 0
       0    .045       0
Bank Sta=280.3,320.93
XS Rating Curve= 0 ,0
Exp/Cntr=0.3,0.1

Type RM Length L Ch R = 1 ,1130.135,83.28,83.34,83.35
XS GIS Cut Line= 2
3110351.4279256810161511.48345943110700.3862172710161055.7543839
#Sta/Elev= 30
       0  772.82      23  773.15      99  772.81   126.5  771.04   143.5  768.29
     170  767.57   182.5  763.89     187  762.97   193.5  762.86     199  761.96
   206.5  759.87   230.5  759.24  249.49  759.37  271.18  760.14  281.49  759.62
  283.49  758.78  285.49  758.52  290.99   758.9  296.49  760.14  302.49  760.78
  304.49  761.64  311.32  762.82  320.99  766.09  336.99  777.19  353.99  787.97
  363.49  795.98  389.99  802.85  442.99  805.73  523.48  805.61  573.98  808.12
#Mann= 1 ,-1 , 0
       0    .045       0
Bank Sta=271.18,311.32
XS Rating Curve= 0 ,0
Exp/Cntr=0.3,0.1

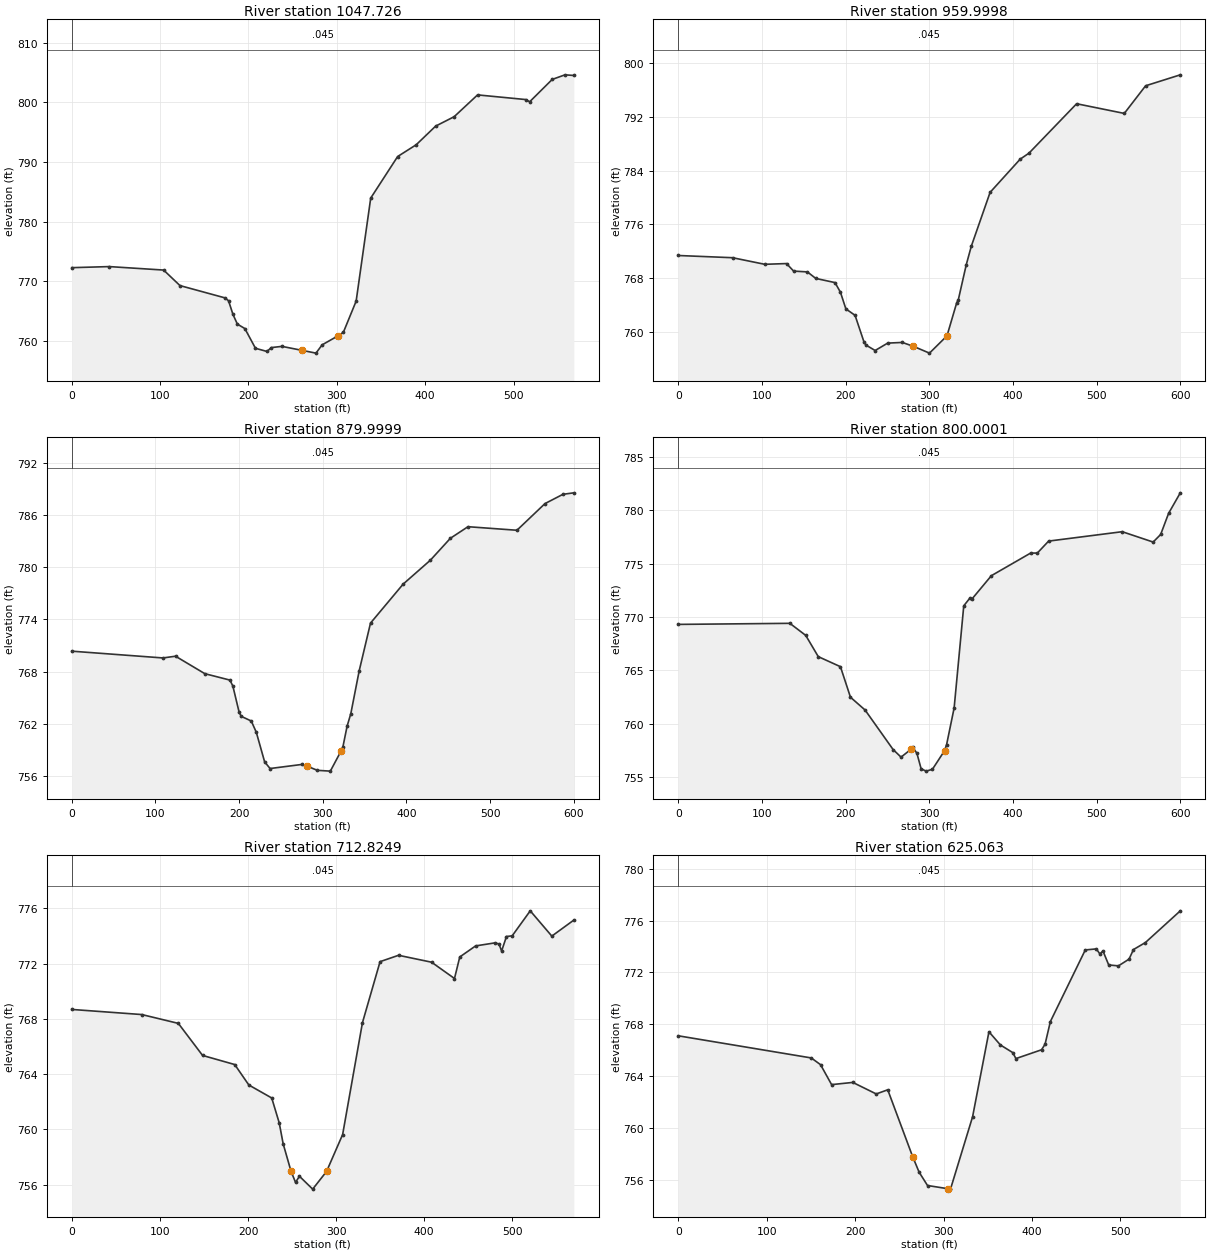
Type RM Length L Ch R = 1 ,1047.726,87.9,87.8,87.75
XS GIS Cut Line= 2
3110413.9281287810161563.56701663110760.28209484 10161113.045936
#Sta/Elev= 30
       0   772.3   42.48  772.48  103.96   771.9  122.45   769.3  173.43  767.24
  177.43  766.76  182.43  764.48  187.42  762.85  195.92   762.1  207.92   758.8
  220.91  758.27  225.91  758.92   237.9  759.12  261.08  758.44  276.39  757.99
  283.39  759.38  301.08  760.86  307.37  761.46  321.87   766.7  338.36  783.95
  368.85  790.91  389.84  792.88  411.83     796  432.82  797.58  459.31  801.23
  513.79  800.45  518.29  800.08  543.78  803.82  558.27  804.59  568.27  804.48
#Mann= 1 ,-1 , 0
       0    .045       0
Bank Sta=261.08,301.08
XS Rating Curve= 0 ,0
Exp/Cntr=0.3,0.1

Type RM Length L Ch R = 1 ,959.9998,78.83,80.06,81.29
XS GIS Cut Line= 2
3110473.5126552610161631.02948013110837.9827268410161154.4146197
#Sta/Elev= 30
       0  771.36   64.95  771.03  103.41  770.05  129.39  770.16  137.89  769.04
  154.37  768.92  164.36  767.95  187.34  767.33  193.84   765.9  200.33  763.42
  211.32  762.46  221.82  758.56  224.31  758.04   235.3  757.23  250.29  758.33
  267.78  758.43  281.07  757.85  300.25  756.84  321.16  759.41  332.72   764.3
  334.72  764.78  344.21  769.99  350.21  772.73  372.69  780.75  408.66  785.69
  419.15  786.58   476.1  793.93  533.06  792.49  558.53   796.6     600  798.23
#Mann= 1 ,-1 , 0
       0    .045       0
Bank Sta=281.07,321.16
XS Rating Curve= 0 ,0
Exp/Cntr=0.3,0.1

Type RM Length L Ch R = 1 ,879.9999,78.36,80.11,81.85
XS GIS Cut Line= 2
3110528.6116264510161675.44671413110907.5577189310161210.2589962
#Sta/Elev= 30
       0  770.35     109  769.57     124  769.77     159  767.76     189  767.02
   192.5  766.34     200  763.32   202.5  762.85   214.5  762.31   220.5  761.02
   230.5   757.6     237  756.84     275  757.31  281.58   757.1   293.5  756.63
     309  756.54  321.61  758.82     324  759.32     329   761.7   333.5  763.17
   343.5   768.1     357  773.58     396  778.07   428.5  780.82   452.5  783.35
   473.5  784.68     532  784.27   565.5  787.34     587  788.41     600  788.58
#Mann= 1 ,-1 , 0
       0    .045       0
Bank Sta=281.58,321.61
XS Rating Curve= 0 ,0
Exp/Cntr=0.3,0.1

Type RM Length L Ch R = 1 ,800.0001,88.47,89.05,89.05
XS GIS Cut Line= 2
3110579.4402649410161718.9561415  3110978.29412610161270.7198333
#Sta/Elev= 30
       0  769.31  133.39  769.41  152.37  768.28  167.36  766.29  193.84  765.35
  205.83  762.49  223.31  761.29  256.79  757.59  266.28  756.88  278.22  757.62
  280.27  757.82  285.26  757.23  290.26  755.79  296.25  755.57  303.75  755.74
  318.31  757.49  320.73  758.06  329.72  761.49  341.22  771.05  348.21  771.74
  350.71  771.66  374.19  773.87  421.15  775.99  429.14  775.99  442.63  777.11
  530.56  777.99  567.53  777.02  576.52  777.73  586.01  779.71     600  781.63
#Mann= 1 ,-1 , 0
       0    .045       0
Bank Sta=278.22,318.31
XS Rating Curve= 0 ,0
Exp/Cntr=0.3,0.1

Type RM Length L Ch R = 1 ,712.8249,90.08,87.43,85.34
XS GIS Cut Line= 2
3110649.6051508510161761.48361553111035.8898113410161342.6468548
#Sta/Elev= 30
       0  768.69   79.47  768.32  120.95  767.68  148.44  765.36  184.93   764.7
  200.92  763.22  226.91  762.28  235.41  760.48   239.9  758.96  248.75  756.99
   253.9  756.17   258.4  756.61  273.39  755.68  289.13  756.96  307.38  759.63
  329.87  767.73  349.86  772.15  370.85  772.61  408.34  772.11  434.32  770.93
  440.32  772.49  458.31  773.29  480.31  773.51   484.8  773.43   487.8  772.92
   493.3  773.97   499.8  774.02  520.29  775.83  544.78     774  569.77  775.16
#Mann= 1 ,-1 , 0
       0    .045       0
Bank Sta=248.75,289.13
XS Rating Curve= 0 ,0
Exp/Cntr=0.3,0.1

Type RM Length L Ch R = 1 ,625.063 ,62.09,65.07,68.08
XS GIS Cut Line= 2
3110723.3897801910161833.09797363111081.4628829410161392.5598127
#Sta/Elev= 30
       0   767.1  150.42  765.39  160.92  764.87  173.41  763.33   197.4   763.5
  223.88  762.61  236.88  762.93  265.05  757.77  272.36  756.57  281.85  755.54
  305.13  755.29  307.84  755.26  332.83  760.85  351.32  767.41  364.31  766.39
   378.3   765.8   381.8  765.34  410.78  766.02  414.78  766.45  420.78   768.2
  460.26  773.73  472.75  773.81  476.75  773.42  480.25  773.65  486.74  772.57
  497.74   772.5  509.73  773.02  514.73  773.76  528.22   774.3   567.7  776.75
#Mann= 1 ,-1 , 0
       0    .045       0
Bank Sta=265.05,305.13
XS Rating Curve= 0 ,0
Exp/Cntr=0.3,0.1

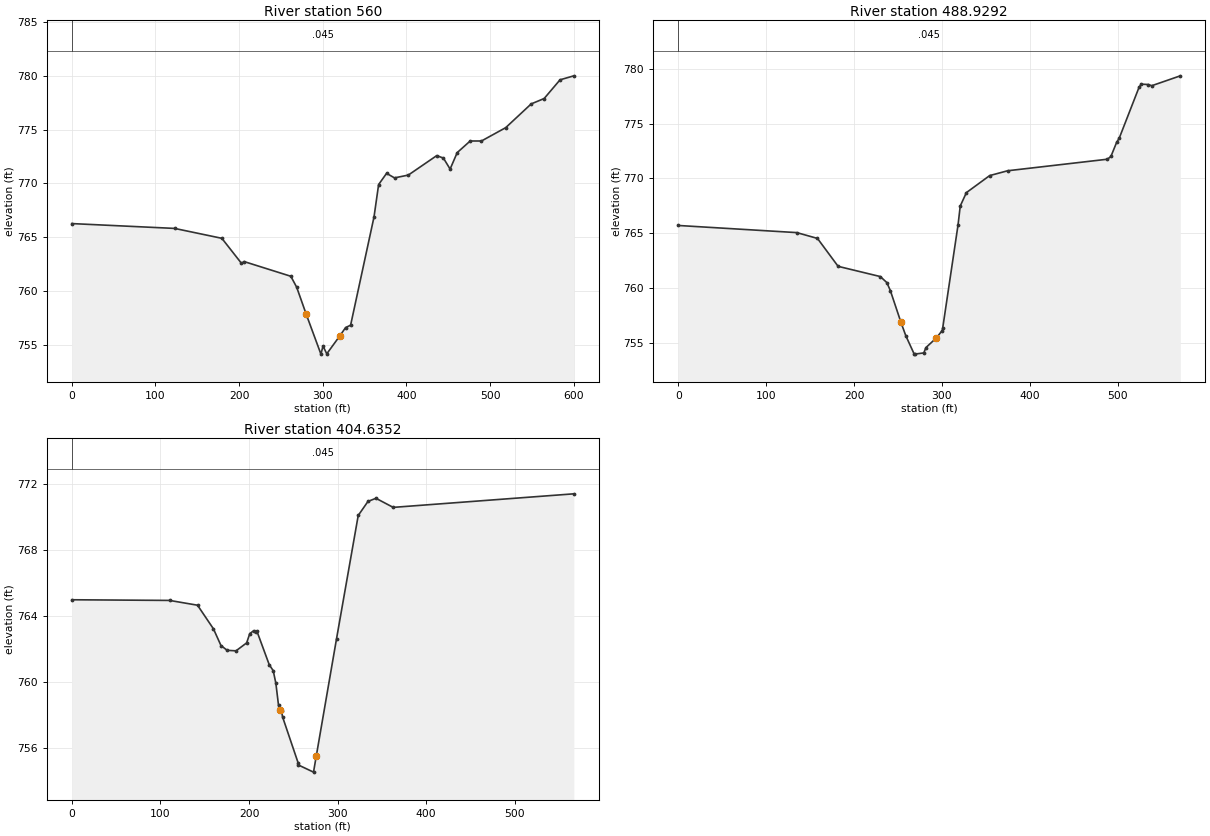
Type RM Length L Ch R = 1 ,560     ,68.71,71.16,73.6
XS GIS Cut Line= 2
3110744.2781898410161874.52210343111156.6356328410161438.6765184
#Sta/Elev= 30
       0  766.27   122.9  765.82  179.35   764.9  202.83  762.57  205.83  762.74
  261.78  761.37  268.78  760.35  280.26  757.82  297.75  754.13  300.25  754.88
  304.75  754.16  320.26  755.82  327.23   756.6  333.22  756.82   361.2  766.89
   366.7   769.9  376.19  770.94  385.68  770.52  402.17  770.78  436.14  772.59
  444.13  772.36  452.13  771.34  460.62  772.87  476.11  773.95   489.6  773.95
  518.57  775.19  549.05   777.4  564.53   777.9  583.52  779.64     600  780.01
#Mann= 1 ,-1 , 0
       0    .045       0
Bank Sta=280.26,320.26
XS Rating Curve= 0 ,0
Exp/Cntr=0.3,0.1

Type RM Length L Ch R = 1 ,488.9292,81.53,84.41,87.3
XS GIS Cut Line= 2
 3110804.782990110161890.06308283111221.4498076710161499.4382078
#Sta/Elev= 30
       0  765.72  134.91  765.07   158.4  764.54  181.88     762  229.85  761.07
  237.35  760.52  241.35  759.78  253.24  756.93  258.84  755.69  268.33  754.03
  268.83  754.01  279.32  754.12  281.82  754.61   293.7  755.49  300.31  756.16
  300.81  756.36   318.3  765.77   320.8  767.49  327.79  768.71  354.28  770.26
  374.76   770.7  488.19  771.75  492.19     772  498.68  773.28  501.68  773.67
  524.17  778.29  526.67  778.58  534.66  778.55  538.66  778.44  571.14  779.34
#Mann= 1 ,-1 , 0
       0    .045       0
Bank Sta=253.24,293.7
XS Rating Curve= 0 ,0
Exp/Cntr=0.3,0.1

Type RM Length L Ch R = 1 ,404.6352,336.23,404.35,375.68
XS GIS Cut Line= 2
3110869.8871906110161918.70902283111309.9912972710161561.9380828
#Sta/Elev= 30
       0  764.97  110.41  764.93  141.89  764.64  159.87  763.21  168.37   762.2
  175.36  761.91  185.35  761.88  197.34  762.36  200.84  762.92  205.34   763.1
  207.34  763.01  208.83  763.08  222.82  761.04  227.32  760.68  230.32  759.91
  233.31  758.58  233.81  758.44   235.5  758.31  236.81  758.21  237.81  757.89
   255.3  755.12   255.8  754.97  272.78  754.54  275.99  755.54  298.76  762.61
  323.24  770.07  334.23  770.92  343.23  771.11  362.71  770.56  566.55  771.38
#Mann= 1 ,-1 , 0
       0    .045       0
Bank Sta=235.5,275.99
XS Rating Curve= 0 ,0
Exp/Cntr=0.3,0.1

River Reach=Brushy          ,Upper
Reach XY= 13
3110254.5718201710163433.03965563110286.9841569410163325.5661173
3110309.3847026810163224.46920663110356.6424821910163013.0096558
3110377.1647508410162878.77632843110429.8660890210162745.3235113
3110469.4788706910162652.89390623110553.9577043710162532.5850917
3110683.8281795110162398.8727607 3110790.560577610162323.9089998
3111082.1121598510162143.77911083111262.01173443 10162068.028278
3111354.80255935 10162036.209444

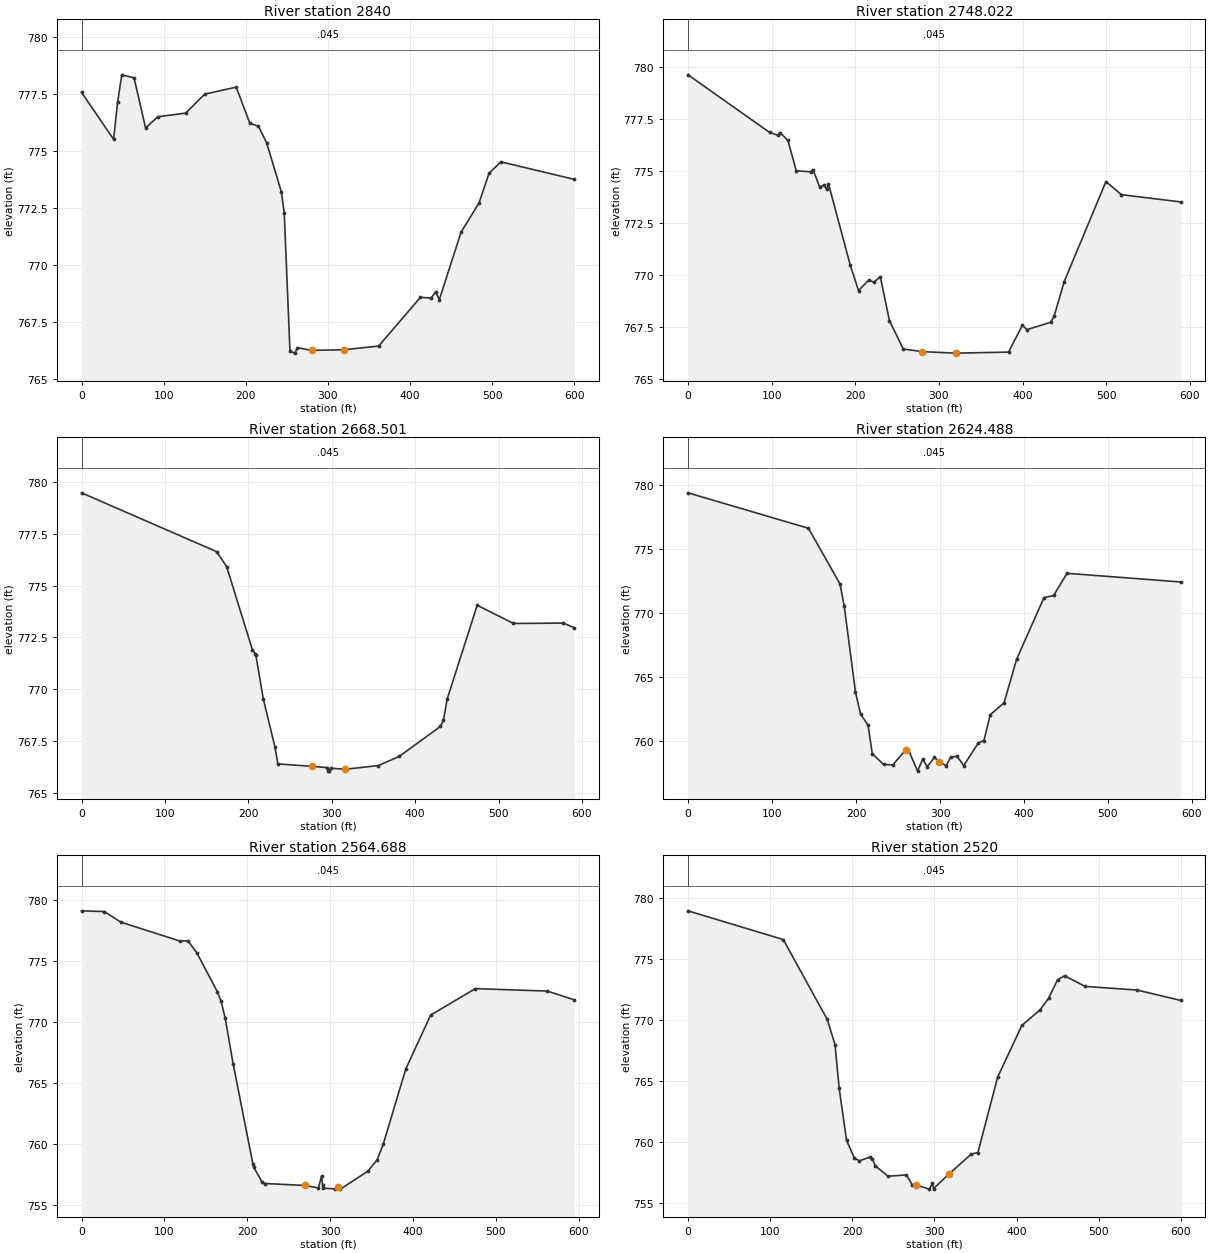
Type RM Length L Ch R = 1 ,2840    ,93.38,91.98,90.58
XS GIS Cut Line= 2
3110562.6528969410163450.49729793109988.2081796810163277.2538779
#Sta/Elev= 30
       0  777.57   38.97  775.51   43.96  777.15   48.96  778.34   63.95  778.21
   77.94  776.01   92.92   776.5  126.89  776.66  149.88  777.49  188.34   777.8
  204.83  776.22  215.32  776.08  225.31  775.36   243.3   773.2  246.79  772.28
  253.79   766.2  259.78  766.12  262.78  766.36     280  766.24     320  766.27
   361.7  766.43  412.66  768.57  425.65  768.54  431.14  768.81  435.64  768.47
  462.12  771.43   484.1  772.72  496.09  774.01  510.58  774.52     600  773.75
#Mann= 1 ,-1 , 0
       0    .045       0
Bank Sta=280,320
XS Rating Curve= 0 ,0
Exp/Cntr=0.3,0.1

Type RM Length L Ch R = 1 ,2748.022,79.66,79.68,79.68
XS GIS Cut Line= 2
3110588.5304698610163351.42498943110018.9627113610163201.1536364
#Sta/Elev= 30
       0  779.64   97.43  776.87  107.42  776.73  109.92  776.86  119.41  776.48
   129.4  775.02  146.89  774.97  149.39  775.08  157.38  774.24  162.38  774.32
  165.88  774.12  167.87   774.4  193.85  770.49  203.85  769.25  215.84  769.75
  222.33  769.66  229.83  769.92  240.82   767.8  257.31  766.44  280.22  766.31
  320.26  766.24  383.21  766.29   399.7  767.58   405.2  767.37  433.67  767.73
  437.67  768.02  449.66  769.68  499.62   774.5  518.11  773.87  589.06  773.52
#Mann= 1 ,-1 , 0
       0    .045       0
Bank Sta=280.22,320.26
XS Rating Curve= 0 ,0
Exp/Cntr=0.3,0.1

Type RM Length L Ch R = 1 ,2668.501,42.69,43.9,45.11
XS GIS Cut Line= 2
3110605.7472989310163273.8585435 3110034.587680110163123.0287927
#Sta/Elev= 24
       0  779.48  161.93  776.64  173.92  775.92  204.91  771.89  208.41  771.71
  208.91  771.65   217.9  769.53   231.9   767.2   235.4  766.39  275.96  766.27
  294.37  766.21  295.87  766.05  296.37  766.04  299.37  766.18  316.13  766.13
  355.84  766.31  380.83  766.75  430.31   768.2  433.81  768.49  438.31  769.52
  474.29  774.05  517.78  773.17  577.75  773.19  590.74  772.96
#Mann= 1 ,-1 , 0
       0    .045       0
Bank Sta=275.96,316.13
XS Rating Curve= 0 ,0
Exp/Cntr=0.3,0.1

Type RM Length L Ch R = 1 ,2624.488,62.49,60.37,58.25
Node Name=USDamonBC
XS GIS Cut Line= 2
3110600.5599733610163235.87600793110038.0601141210163069.2093465
#Sta/Elev= 30
       0  779.42  143.42  776.64   180.9  772.28   185.9  770.58  199.39   763.8
  205.38  762.08  214.38   761.2  219.38  758.96  232.87  758.12  243.86  758.09
  259.07  759.26  262.35  759.28  273.35   757.6  279.34  758.54  284.84  757.95
  293.34  758.67  299.38  758.34  307.33  758.02  312.83  758.71  320.32  758.75
  328.32  758.04  345.81  759.83   352.3  759.99   359.8  762.02  376.29  762.96
  391.28  766.38  423.76   771.2  435.26  771.37  451.25  773.11  586.67  772.43
#Mann= 1 ,-1 , 0
       0    .045       0
Bank Sta=259.07,299.38
XS Rating Curve= 0 ,0
Exp/Cntr=0.3,0.1

Type RM Length L Ch R = 1 ,2564.688,45.46,44.83,44.2
XS GIS Cut Line= 2
3110624.86569902 10163164.6953763110046.3645594410163025.8852862
#Sta/Elev= 30
       0  779.15    27.5  779.09   47.49  778.22  118.48  776.68  128.48  776.69
  139.48  775.67  163.98  772.51  168.48  771.74  173.48  770.33  182.98  766.62
  206.97  758.36  207.97  758.11  217.97  756.92  221.97  756.79  270.11  756.63
  285.96  756.43  289.96  757.43  290.96  756.68  291.46  756.41  305.96  756.35
  310.21  756.47  312.46  756.33  345.45  757.79  356.95  758.74  364.45  760.06
  391.45  766.18  421.44   770.6  475.44  772.77  562.43  772.57  594.92  771.85
#Mann= 1 ,-1 , 0
       0    .045       0
Bank Sta=270.11,310.21
XS Rating Curve= 0 ,0
Exp/Cntr=0.3,0.1

Type RM Length L Ch R = 1 ,2520    ,40.06,40.06,40.21
XS GIS Cut Line= 2
3110640.6438826910163117.71056193110055.0886233410162986.8482908
#Sta/Elev= 30
       0  778.93     116  776.58   169.5  770.05     179  767.99     184  764.44
     193  760.17   202.5  758.72   208.5  758.48     221  758.78   224.5  758.66
     228  758.08   243.5  757.23     266  757.33     273  756.51  277.73   756.5
     294  756.17   297.5  756.65     299  756.22  317.79  757.41     345  759.04
     353  759.16     377  765.33   406.5  769.56   428.5  770.82     439  771.78
     450  773.29   458.5  773.62   483.5  772.75     547  772.45     600   771.6
#Mann= 1 ,-1 , 0
       0    .045       0
Bank Sta=277.73,317.79
XS Rating Curve= 0 ,0
Exp/Cntr=0.3,0.1

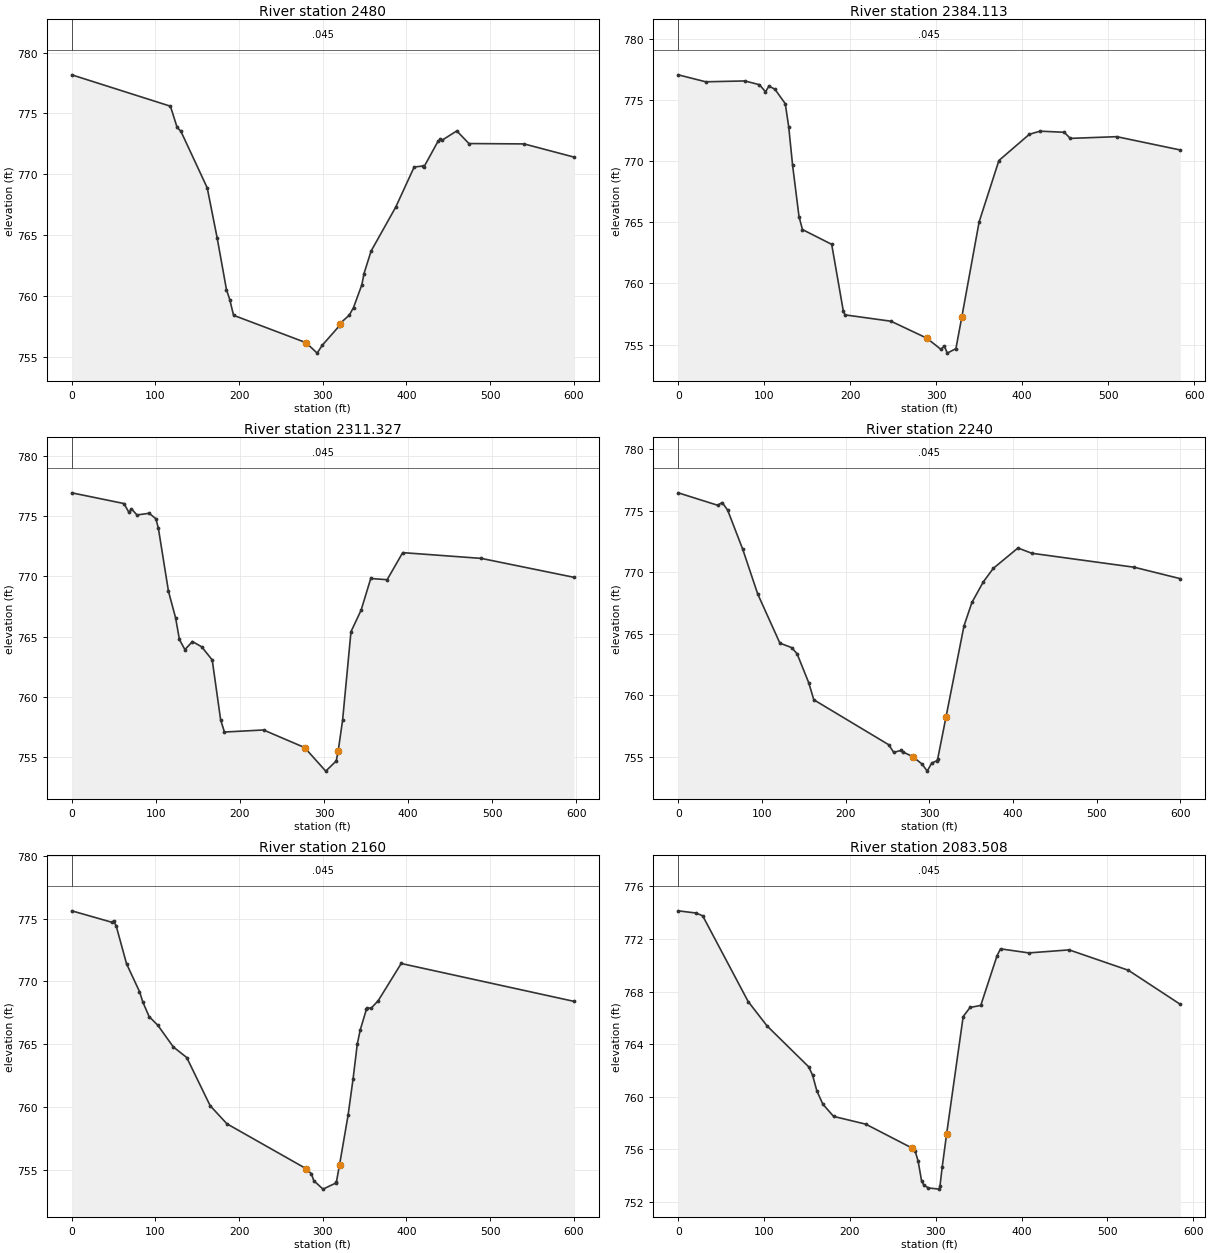
Type RM Length L Ch R = 1 ,2480    ,98.43,97.93,97.28
XS GIS Cut Line= 2
3110649.3682746910163078.67356643110063.8126872810162947.8112953
#Sta/Elev= 30
       0  778.17   117.9  775.59  125.89  773.85  130.39  773.53  161.87  768.88
  173.86  764.72  184.85  760.52  188.84  759.68  193.34   758.4  279.96  756.15
  293.26  755.29  299.25  755.93  319.23  757.49  320.51  757.72  331.72  758.42
  336.72  759.04  346.71  760.92  349.21  761.83   357.7  763.68  387.18   767.3
  409.16  770.59  419.15  770.67  420.65  770.57  437.63   772.7  440.63  772.87
  442.63   772.8  460.12  773.56   474.6  772.52  540.55  772.49     600  771.41
#Mann= 1 ,-1 , 0
       0    .045       0
Bank Sta=279.96,320.51
XS Rating Curve= 0 ,0
Exp/Cntr=0.3,0.1

Type RM Length L Ch R = 1 ,2384.113,67.56,73.33,79.1
XS GIS Cut Line= 2
3110665.25111693 10162979.5028333110093.6154491910162860.8757737
#Sta/Elev= 30
       0  777.07   31.99   776.5   77.48  776.57   94.47  776.26  101.47  775.68
  105.47  776.15  112.46  775.89  124.46  774.71  128.46  772.82  132.96  769.68
  140.46  765.46  144.45  764.41  178.44   763.2  191.94  757.75  193.94  757.43
  247.42  756.91  289.19  755.52   305.4  754.61   309.4  754.88   312.9   754.3
   322.9  754.67  329.78  757.27  349.89  765.04  372.88  770.06  408.37  772.21
  420.87  772.46  448.86  772.37  455.86  771.87  509.84  772.01  583.82  770.92
#Mann= 1 ,-1 , 0
       0    .045       0
Bank Sta=289.19,329.78
XS Rating Curve= 0 ,0
Exp/Cntr=0.3,0.1

Type RM Length L Ch R = 1 ,2311.327,70.17,71.33,72.48
XS GIS Cut Line= 2
3110668.2681712810162949.41759133110106.9379290910162746.2923414
#Sta/Elev= 30
       0  776.95   61.99  776.06   67.99  775.32   70.99  775.62   77.49  775.11
   91.99  775.25   99.99   774.8  102.99     774  114.99  768.76  123.49  766.55
  127.99  764.76  134.49  763.92  143.49  764.59  154.49  764.15  166.99  763.06
  176.99  758.09  181.49  757.07  227.98  757.24  276.82  755.78  301.98  753.82
  314.48  754.67  316.83  755.53  321.97  758.03  331.97  765.41  343.97  767.19
  355.47  769.83  374.97  769.73  393.47  771.98  486.96   771.5  596.95  769.93
#Mann= 1 ,-1 , 0
       0    .045       0
Bank Sta=276.82,316.83
XS Rating Curve= 0 ,0
Exp/Cntr=0.3,0.1

Type RM Length L Ch R = 1 ,2240    ,78.85,80,81.15
XS GIS Cut Line= 2
3110694.3829484310162892.26580283110136.3223847710162671.8843538
#Sta/Elev= 30
       0  776.47      47  775.46    52.5  775.68      59  775.07      77  771.89
      95  768.23   121.5  764.23   135.5  763.87     142  763.37     156     761
     162  759.62   251.5  755.96   257.5  755.34   266.5   755.5   268.5  755.37
     280     755   291.5  754.38   297.5  753.81     303  754.47   309.5  754.67
     310  754.78     320  758.22   341.5  765.64     351  767.55   364.5  769.21
   376.5  770.32     406  771.98   422.5  771.55     545  770.41     600  769.48
#Mann= 1 ,-1 , 0
       0    .045       0
Bank Sta=280,320
XS Rating Curve= 0 ,0
Exp/Cntr=0.3,0.1

Type RM Length L Ch R = 1 ,2160    ,72.75,76.49,80.23
XS GIS Cut Line= 2
3110721.55809093 10162826.2866043110170.0710049310162589.9343864
#Sta/Elev= 30
       0  775.62   47.96  774.71   49.96  774.79   52.96  774.45   65.45  771.41
   80.93   769.2   84.93  768.36   92.42  767.21  102.91  766.51   121.4  764.79
  137.39  763.95  165.36  760.12  185.35  758.68     280  755.11  286.26  754.71
  289.26  754.15  300.25  753.48  315.74  753.97  316.24  754.05     320  755.41
  330.23  759.37  336.22  762.28  341.22  765.03  344.71  766.14  352.21  767.81
  352.71  767.89   357.7  767.87   366.2  768.47  393.67  771.43     600  768.42
#Mann= 1 ,-1 , 0
       0    .045       0
Bank Sta=280,320
XS Rating Curve= 0 ,0
Exp/Cntr=0.3,0.1

Type RM Length L Ch R = 1 ,2083.508,78.93,83.51,88.09
XS GIS Cut Line= 2
3110735.97669727 10162779.2788243110222.0876331910162499.7646193
#Sta/Elev= 30
       0  774.14      21  773.97    28.5  773.76    81.5  767.24   103.5  765.39
     152  762.28   156.5  761.65   161.5  760.45   168.5  759.44     181  758.51
   218.5  757.92  272.49   756.1  275.99  755.88  279.49  755.12  283.49  753.62
  285.99   753.3  291.49  753.07  303.99  752.98  304.99  753.23  307.49  754.63
  312.76   757.2  331.99   766.1  339.99  766.79  352.49  766.95  371.49  770.73
  375.49  771.25  408.49  770.94  455.49  771.17  524.49  769.62  584.99  767.03
#Mann= 1 ,-1 , 0
       0    .045       0
Bank Sta=272.49,312.76
XS Rating Curve= 0 ,0
Exp/Cntr=0.3,0.1

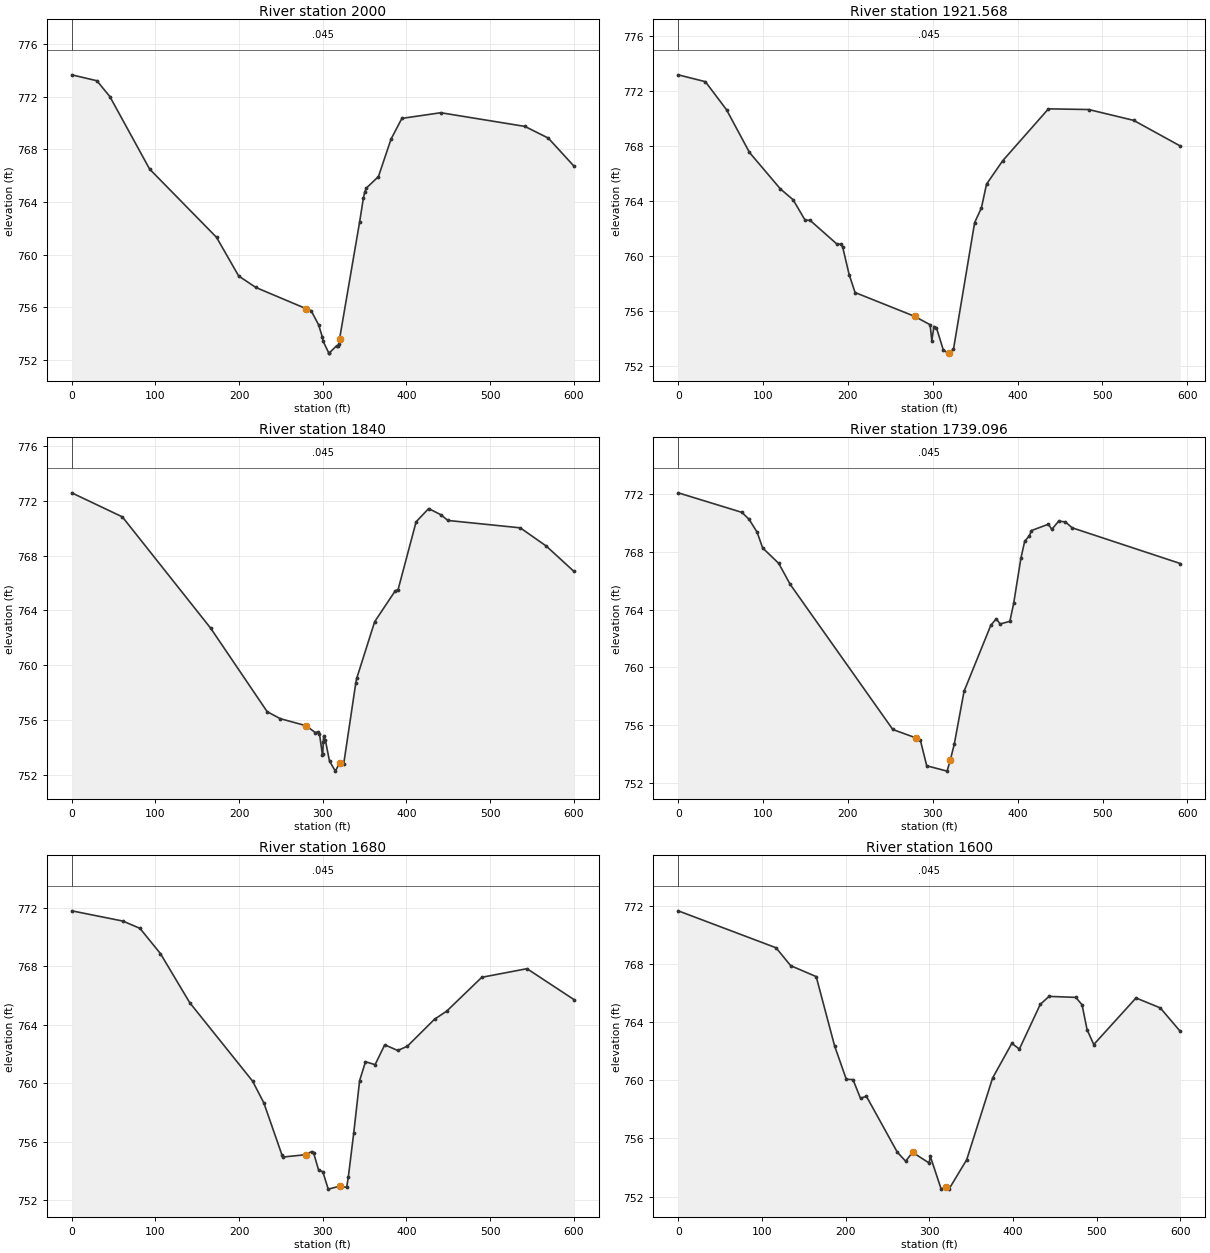
Type RM Length L Ch R = 1 ,2000    ,75.15,78.43,81.71
XS GIS Cut Line= 2
3110772.4198658510162743.51347563110281.3850867710162398.7169211
#Sta/Elev= 29
       0  773.66      30  773.21    45.5  772.01      93   766.5     173  761.31
   199.5  758.37     220   757.5     280  755.89     286  755.74     295  754.66
   299.5  753.72   300.5   753.4     307  752.54   307.5  752.51   316.5  753.07
   318.5  753.07     319   753.2     320  753.58     344  762.48   348.5  764.29
     350  764.73     352  765.05   366.5  765.93   381.5  768.77   394.5  770.35
     441  770.78   541.5  769.74   569.5  768.85     600  766.73
#Mann= 1 ,-1 , 0
       0    .045       0
Bank Sta=280,320
XS Rating Curve= 0 ,0
Exp/Cntr=0.3,0.1

Type RM Length L Ch R = 1 ,1921.568,78.49,81.57,84.65
XS GIS Cut Line= 2
3110805.4211121810162701.15365223110350.56014526 10162322.681312
#Sta/Elev= 30
       0   773.2   31.99   772.7   56.97  770.65   83.96  767.54  120.44  764.88
  135.44  764.09  149.43  762.61  155.43  762.59  187.41  760.84  191.41  760.87
  193.91  760.62  201.41  758.64   208.4  757.33  278.65  755.59  296.86  754.98
  298.86  753.81  301.36  754.85  304.36  754.75  312.36  753.15  317.85  752.91
  318.77  752.94  324.35  753.18  349.34  762.43  357.33   763.5  363.33  765.23
  382.32  766.93   436.3  770.72  483.78  770.67  536.75  769.88  591.73  768.01
#Mann= 1 ,-1 , 0
       0    .045       0
Bank Sta=278.65,318.77
XS Rating Curve= 0 ,0
Exp/Cntr=0.3,0.1

Type RM Length L Ch R = 1 ,1840    ,95.92,100.9,105.89
XS GIS Cut Line= 2
3110847.8327727610162660.60156793110417.4307464410162242.5656586
#Sta/Elev= 30
       0   772.6    60.5  770.84     166   762.7   233.5   756.6     249  756.09
     280  755.57     291  755.07   294.5  755.12     296  754.99   299.5  753.46
     300  753.49   300.5  754.37     301  754.81     303  754.53     308  752.98
     315  752.25     320  752.84     325  752.79   339.5  758.73   340.5  759.03
     362  763.18   386.5  765.43     390  765.53   411.5  770.48   426.5  771.45
     441     771   449.5  770.58     536  770.04     567  768.71     600  766.86
#Mann= 1 ,-1 , 0
       0    .045       0
Bank Sta=280,320
XS Rating Curve= 0 ,0
Exp/Cntr=0.3,0.1

Type RM Length L Ch R = 1 ,1739.096,56.55,59.1,61.64
XS GIS Cut Line= 2
3110894.3218530110162617.63380613110524.1710185110162156.0146506
#Sta/Elev= 30
       0  772.08   74.96  770.73   83.46  770.25   92.95  769.36   99.45  768.27
  118.44   767.2  131.93  765.75  252.87  755.71  280.57  755.12  285.35  754.97
  292.85   753.2  316.84  752.83  320.65   753.6  325.33   754.7  336.83  758.35
  368.31  762.91  374.81  763.37   379.3  763.01   390.8  763.19   395.3  764.43
  403.79  767.54  408.29  768.73  413.79  769.11  416.29  769.47  436.28  769.91
  440.27  769.55  448.27  770.12  456.27  770.07  464.26  769.66   591.7  767.19
#Mann= 1 ,-1 , 0
       0    .045       0
Bank Sta=280.57,320.65
XS Rating Curve= 0 ,0
Exp/Cntr=0.3,0.1

Type RM Length L Ch R = 1 ,1680    ,77.64,80,82.36
XS GIS Cut Line= 2
 3110927.054727210162594.6436946 3110582.202726610162103.6479574
#Sta/Elev= 30
       0   771.8      61   771.1    81.5   770.6     106  768.87     141  765.51
     216  760.15   229.5  758.66     251  755.12     253  754.95     280  755.11
   286.5  755.32     289  755.23     295  754.05     300  753.94   306.5  752.75
     320  752.95   328.5  752.87   330.5  753.58     337  756.61     344  760.18
     351  761.47   362.5  761.27     374  762.63   389.5  762.24     401  762.53
   433.5  764.38     448  764.93     490  767.25     544  767.84     600  765.73
#Mann= 1 ,-1 , 0
       0    .045       0
Bank Sta=280,320
XS Rating Curve= 0 ,0
Exp/Cntr=0.3,0.1

Type RM Length L Ch R = 1 ,1600    ,80,80,80
XS GIS Cut Line= 2
3110978.9463556710162560.15754313110663.5821570210162049.7208999
#Sta/Elev= 30
       0  771.64   116.9   769.1  134.39  767.87  164.86  767.12  186.84  762.36
  200.83  760.06  208.83  760.04  217.82  758.75  224.81   758.9  261.78  755.05
  271.77  754.43     280  755.04  299.75  754.31  301.25  754.76  314.24  752.51
     320  752.67  323.73  752.53  344.71  754.53  375.69  760.15  398.67  762.53
  407.66  762.14  432.64  765.21  443.13  765.76   475.1  765.69   482.6  765.18
  488.59  763.47  496.59  762.45  547.04  765.65  576.02  764.97     600  763.35
#Mann= 1 ,-1 , 0
       0    .045       0
Bank Sta=280,320
XS Rating Curve= 0 ,0
Exp/Cntr=0.3,0.1