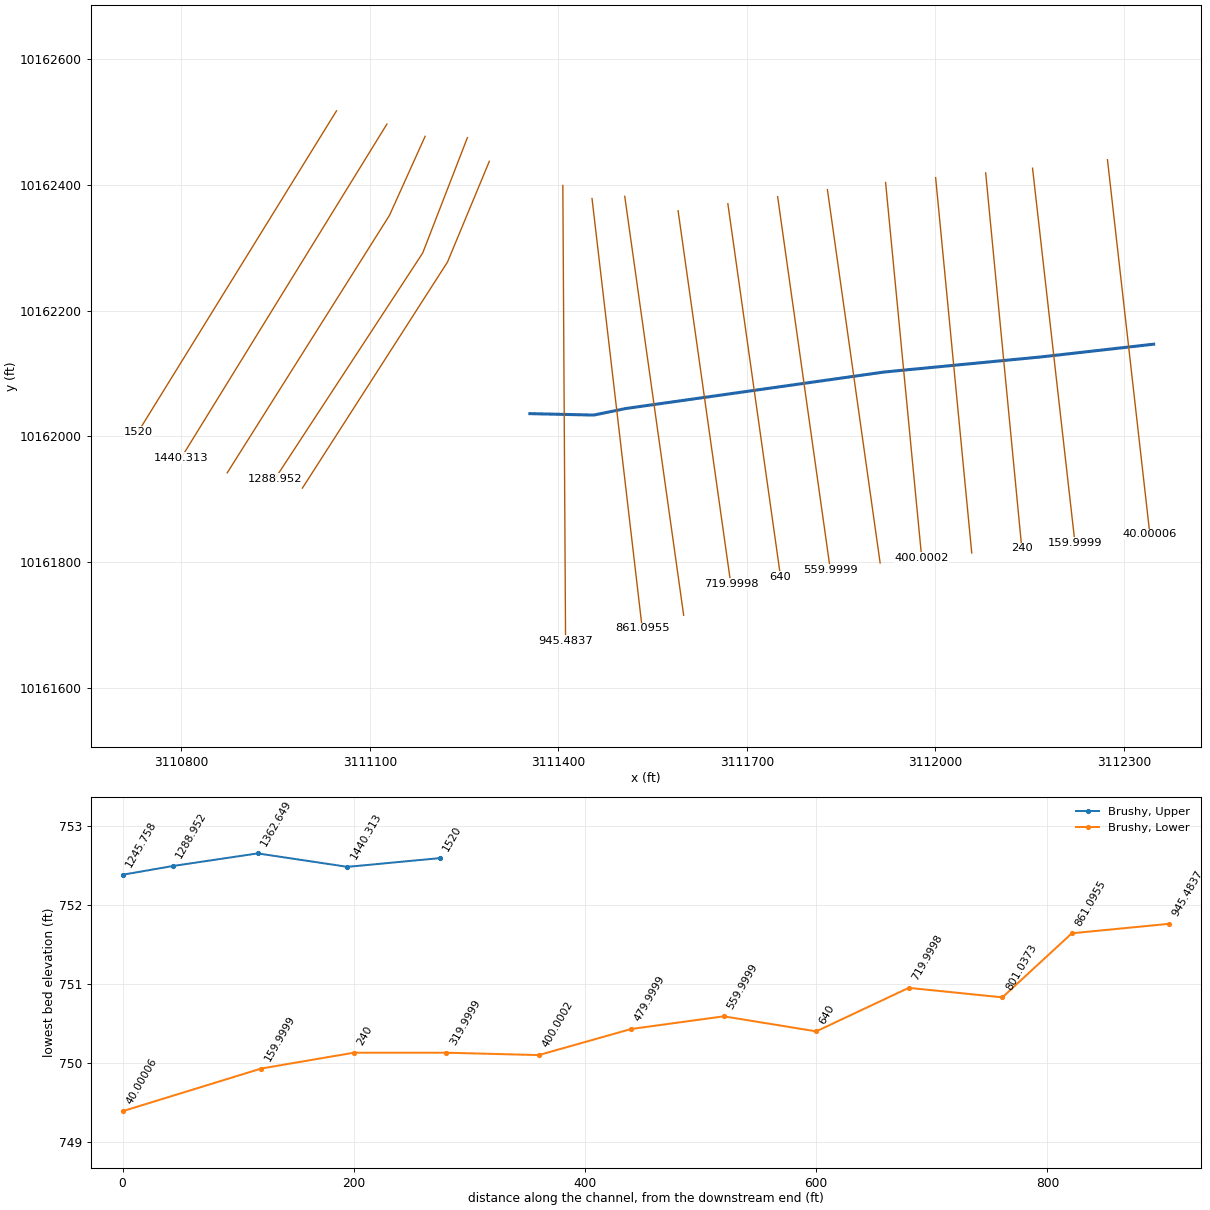
HEC-RAS study UB100yr2.prj: Upper Brushy - 2nd run

--- UB100yr2.g01 (geometry) --- (continued)

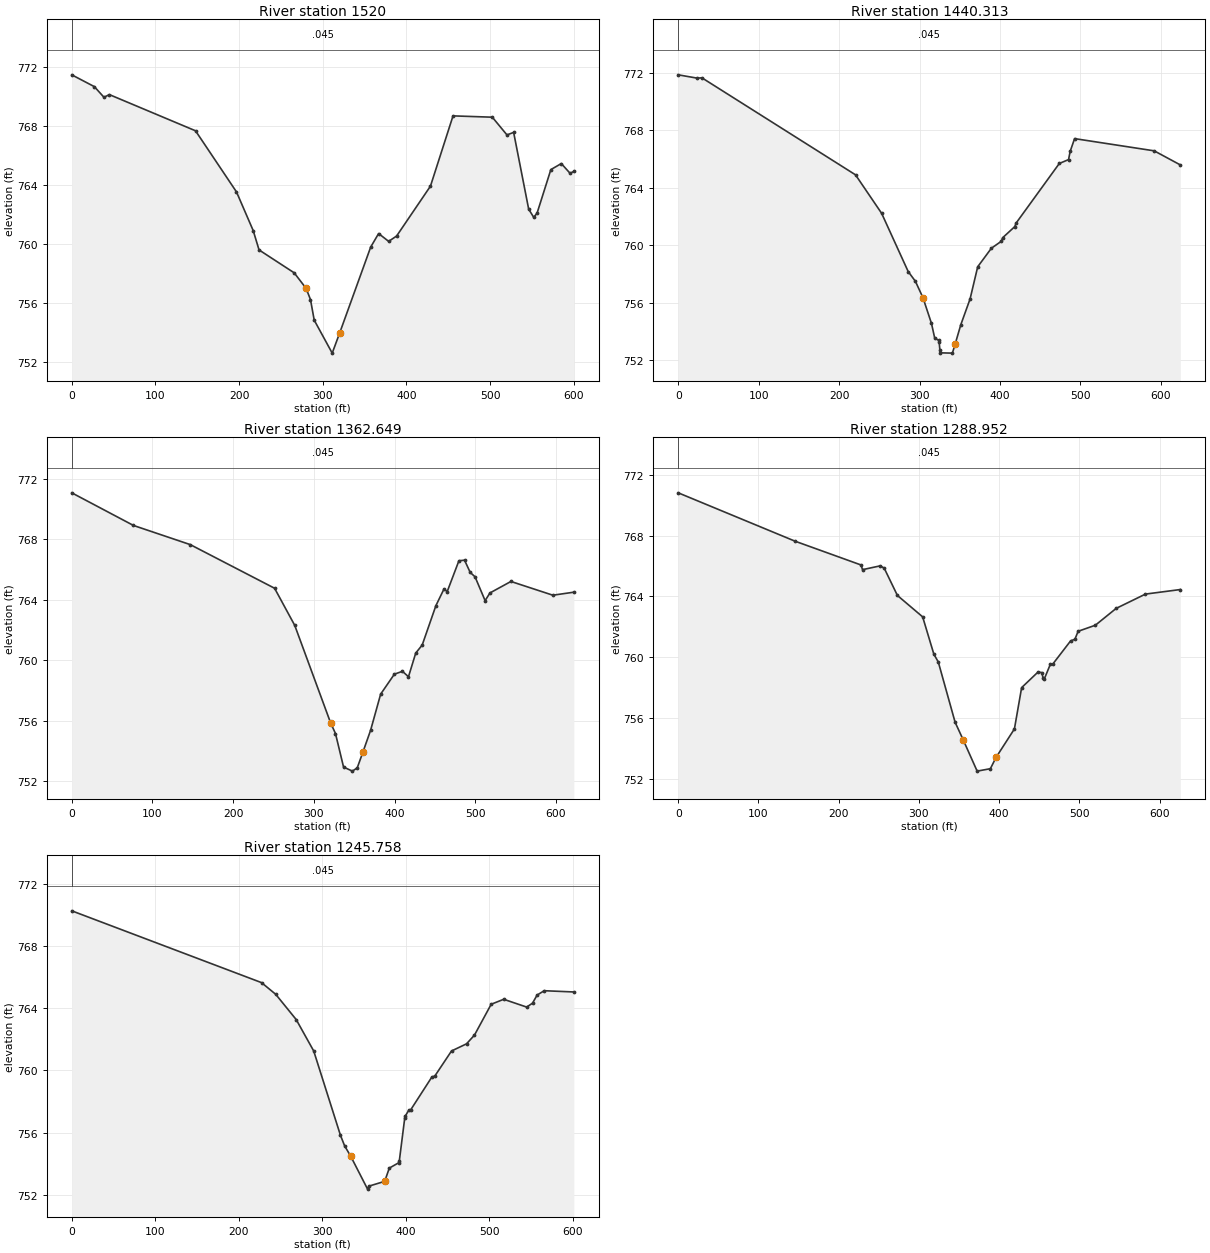
Type RM Length L Ch R = 1 ,1520    ,79.65,79.69,79.73
Node Name=J365
XS GIS Cut Line= 2
3111047.0046185310162518.10907083110731.6404198410162007.6724276
#Sta/Elev= 30
       0  771.44   26.98  770.64   38.47  769.92   44.96   770.1  147.88  767.65
  196.84  763.51  216.82  760.89  223.81  759.58  265.78  758.03     280  756.98
  285.26  756.22  289.76  754.82  311.24  752.59     320  753.93   357.2  759.77
  366.69  760.69  378.68  760.16  388.18  760.52  428.64   763.9  455.62  768.66
  502.58  768.57  520.07  767.37  528.06  767.54  546.04  762.34  552.04  761.79
  556.04  762.07  572.52  765.02  585.01  765.43   595.5  764.77     600   764.9
#Mann= 1 ,-1 , 0
       0    .045       0
Bank Sta=280,320
XS Rating Curve= 0 ,0
Exp/Cntr=0.3,0.1

Type RM Length L Ch R = 1 ,1440.313,78.06,77.66,77.27
XS GIS Cut Line= 2
3111127.26561284 10162497.051042 3110799.698682710161965.6239553
#Sta/Elev= 30
       0  771.85   23.49  771.62   29.49  771.64  220.42  764.89  252.91  762.21
   285.9  758.16  294.89  757.48  304.27  756.34  314.88  754.55  318.88  753.53
  323.88  753.37  324.38  753.27  325.38  752.67  325.88   752.5  340.88  752.48
  344.27   753.1  351.37  754.46  362.87  756.25  372.36  758.49  389.36  759.78
  401.85  760.27  403.35  760.51  418.35  761.28  420.35  761.55  473.83  765.68
  485.32  765.95  487.32  766.52  492.82  767.41  591.79  766.56  624.28  765.58
#Mann= 1 ,-1 , 0
       0    .045       0
Bank Sta=304.27,344.27
XS Rating Curve= 0 ,0
Exp/Cntr=0.3,0.1

Type RM Length L Ch R = 1 ,1362.649,74.45,73.7,72.94
XS GIS Cut Line= 3
3111188.0295989210162477.51991313111131.3338461810162351.8233141
 3110873.129310110161942.0390287
#Sta/Elev= 30
       0  771.08   76.44  768.92  146.89  767.65  251.36  764.76  276.35   762.3
  320.76  755.85  326.83  755.14  336.83  752.92  347.83  752.65  353.82  752.87
  360.76   753.9  370.32  755.35  382.82  757.75  399.81  759.07  409.81  759.26
   417.3   758.9   426.3  760.47   434.3     761  451.29  763.61  461.29  764.71
  465.29  764.54  479.79  766.58  486.78  766.62  493.78  765.81  499.78  765.52
  512.28  763.94  518.27  764.45  544.27  765.21  596.25   764.3  622.24   764.5
#Mann= 1 ,-1 , 0
       0    .045       0
Bank Sta=320.76,360.76
XS Rating Curve= 0 ,0
Exp/Cntr=0.3,0.1

Type RM Length L Ch R = 1 ,1288.952,42.84,43.19,42.91
XS GIS Cut Line= 3
3111255.3040706810162475.34964183111184.1959451710162291.8693658
3110949.3141970910161932.8149658
#Sta/Elev= 30
       0  770.82  145.84  767.63  227.75  766.07  229.74  765.76  251.72  766.01
  256.72  765.86   273.2  764.06  304.67  762.65  318.65  760.19  324.15  759.68
  345.12  755.71  355.46  754.52  372.59  752.49  389.08  752.65  396.12  753.39
  419.05  755.27  428.04  757.99  448.52  759.02  453.01  758.98  455.01   758.6
  456.51  758.59     464  759.55     467  759.55  488.97  761.06  494.47  761.18
  498.46   761.7  519.94   762.1  545.91  763.21  582.38  764.15  625.83  764.45
#Mann= 1 ,-1 , 0
       0    .045       0
Bank Sta=355.46,396.12
XS Rating Curve= 0 ,0
Exp/Cntr=0.3,0.1

Type RM Length L Ch R = 1 ,1245.758,273.89,300.27,329.17
XS GIS Cut Line= 3
3111290.2433052710162437.80640993111223.6105645310162277.3759564
3110992.7169974410161917.6240513
#Sta/Elev= 30
       0  770.25  227.21  765.64  244.21  764.89  268.71  763.27  289.71  761.25
  321.71  755.84  326.71  755.16  334.12  754.48  354.21  752.38  355.71  752.57
  374.72  752.88  380.21  753.73  391.71  754.08  392.21  754.19  398.71  756.95
  399.21  757.06   403.7  757.46   405.7  757.46   431.2  759.58   434.7  759.64
   454.7  761.25   472.7  761.71   482.2  762.27   502.2  764.25   517.2  764.57
   544.7  764.07   551.7  764.32  557.19  764.84  565.69  765.12  601.19  765.04
#Mann= 1 ,-1 , 0
       0    .045       0
Bank Sta=334.12,374.72
XS Rating Curve= 0 ,0
Exp/Cntr=0.3,0.1

River Reach=Brushy          ,Lower
Reach XY= 6
3111354.80255935 10162036.209444 3111456.389626510162033.9394354
3111507.6483822810162044.40037253111918.7656702710162102.4589834
3112168.7835429310162126.51930283112347.4360727710162146.7390786

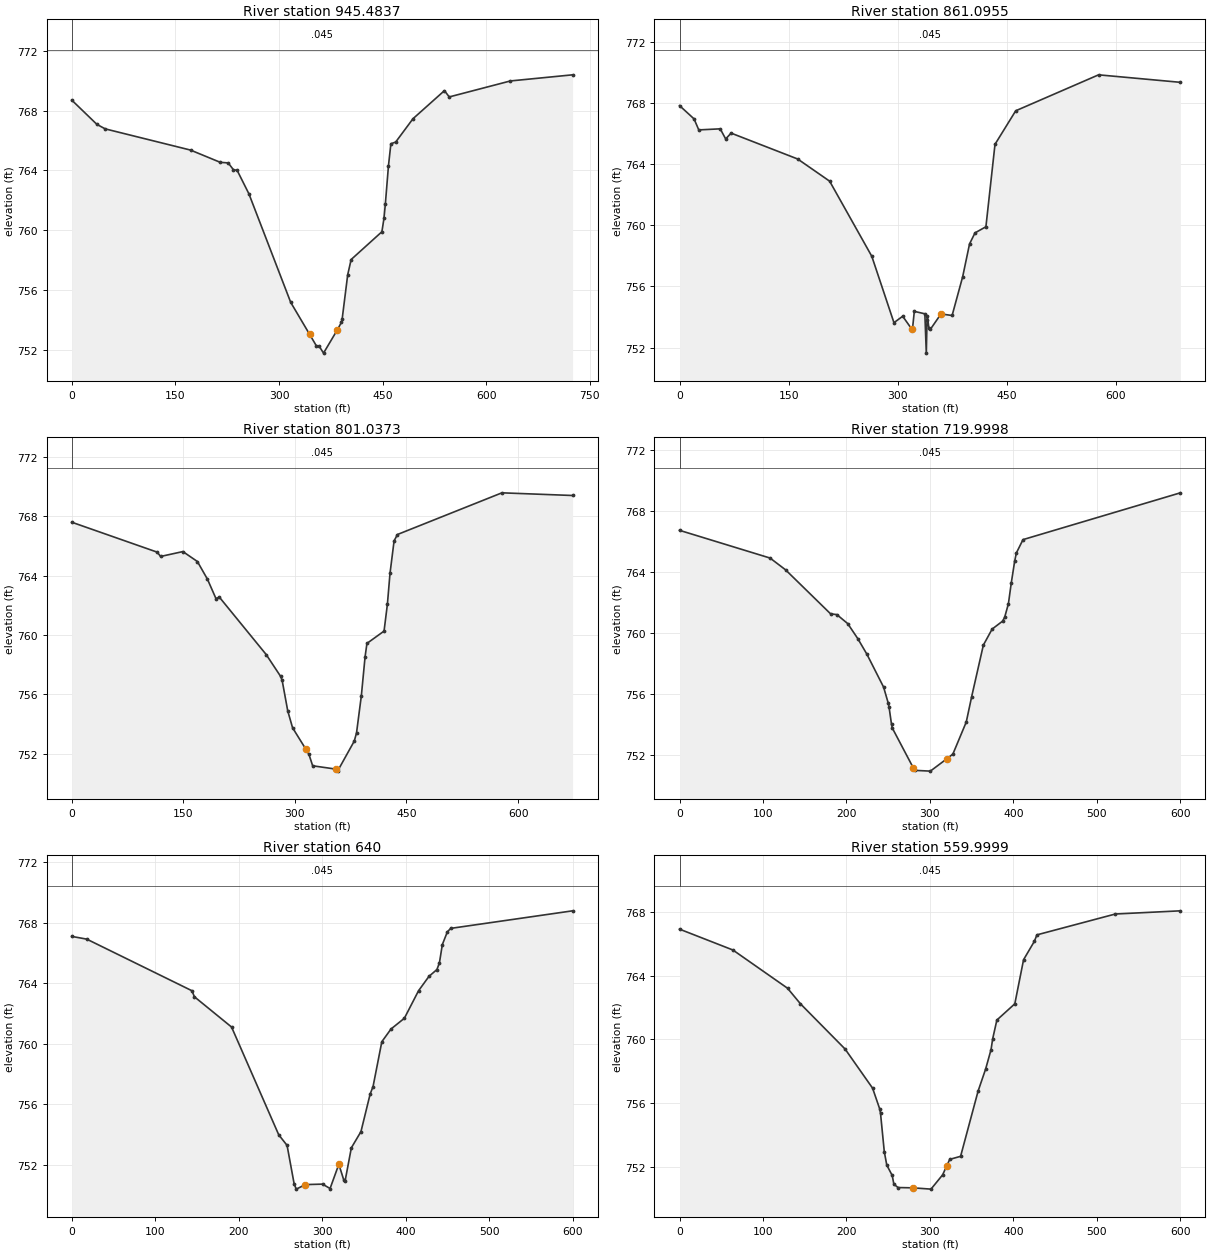
Type RM Length L Ch R = 1 ,945.4837,78.84,84.39,89.94
XS GIS Cut Line= 2
3111407.2135437710162399.39474133111411.55408627 10161674.568435
#Sta/Elev= 30
       0  768.71   36.49  767.08   48.49  766.78  171.96  765.36  214.95  764.54
  226.45   764.5  233.95  764.05  239.45     764  256.44  762.43  316.93  755.16
   344.4  753.01  353.92  752.26  357.92  752.24  364.42  751.76  384.42  753.32
  390.41  753.83  391.41  754.05  399.41  757.01  404.41  758.03   448.9  759.89
   451.9  760.79   453.9  761.75   458.4  764.31   461.9  765.78   468.9   765.9
  493.89  767.46  539.38  769.34  546.38  768.92  634.86  769.99  724.84   770.4
#Mann= 1 ,-1 , 0
       0    .045       0
Bank Sta=344.4,384.42
XS Rating Curve= 0 ,0
Exp/Cntr=0.3,0.1

Type RM Length L Ch R = 1 ,861.0955,58.87,60.06,61.24
Node Name=WalshU
XS GIS Cut Line= 2
3111453.6547238510162378.56144963111533.5157845910161694.5336182
#Sta/Elev= 30
       0  767.82   19.99  766.95   26.49  766.23   55.97   766.3   63.47  765.64
   70.97  766.02  162.42  764.33   206.4  762.88  264.38  757.97  294.86  753.63
  306.86  754.05  319.36  753.21  320.35  753.23  322.85  754.37  337.34  754.21
  339.34  751.64  340.34   753.8  340.84  754.06  342.84   753.3  344.84  753.19
  359.51   754.2  374.82   754.1  389.32  756.63  398.81  758.78  406.31   759.5
   421.3   759.9   433.8  765.29  462.28  767.48  576.23  769.83  688.67  769.34
#Mann= 1 ,-1 , 0
       0    .045       0
Bank Sta=319.36,359.51
XS Rating Curve= 0 ,0
Exp/Cntr=0.3,0.1

Type RM Length L Ch R = 1 ,801.0373,81.01,81.04,81.07
XS GIS Cut Line= 2
3111505.7379530110162382.03388363111599.4880936110161715.3669098
#Sta/Elev= 30
       0  767.61  114.95  765.59  119.45   765.3  149.44  765.63  168.93  764.96
  182.43  763.77  193.92  762.46  198.42  762.56  261.39  758.69  280.89  757.21
  282.89  756.94  290.38  754.89  296.88  753.75  314.58  752.32  318.87  751.96
  323.87  751.19  354.58  750.97  357.35  750.83  379.85  752.86  382.84  753.41
  389.34  755.92  394.34  758.54  396.84  759.44  419.83  760.27  424.33  762.08
  427.83  764.16  433.32  766.35  437.82  766.78  578.26  769.59  673.23  769.41
#Mann= 1 ,-1 , 0
       0    .045       0
Bank Sta=314.58,354.58
XS Rating Curve= 0 ,0
Exp/Cntr=0.3,0.1

Type RM Length L Ch R = 1 ,719.9998,80,80,80
XS GIS Cut Line= 2
3111590.62131342 10162359.0946253111674.5217361710161764.9898421
#Sta/Elev= 30
       0  766.75   108.5  764.93     127  764.16     181  761.27   188.5  761.22
   201.5  760.63   213.5  759.65   224.5  758.62   244.5  756.46     250  755.42
     251  755.16     254  754.01     255  753.77     280  751.17     282     751
   300.5  750.95     320  751.75   327.5  752.07   343.5  754.17     350  755.84
     364  759.22   374.5  760.27     387  760.79   389.5  761.04     394  761.93
   397.5  763.32   401.5  764.72   403.5  765.26   411.5  766.14  600.01  769.21
#Mann= 1 ,-1 , 0
       0    .045       0
Bank Sta=280,320
XS Rating Curve= 0 ,0
Exp/Cntr=0.3,0.1

Type RM Length L Ch R = 1 ,640     ,80,80,80
XS GIS Cut Line= 2
3111669.8353938510162370.2812824 3111753.735816610161776.1764995
#Sta/Elev= 30
       0   767.1      18  766.92     144  763.51     147  763.11   191.5  761.11
     248  753.99     258  753.29   266.5  750.74     269   750.4     280   750.7
   300.5  750.73   309.5  750.44     320  752.04     326  750.99   327.5  750.94
     335  753.13   346.5   754.2   357.5  756.68     361  757.18   371.5  760.14
   382.5  760.98   398.5  761.69   415.5  763.51     428  764.46   437.5  764.91
   440.5  765.35     444  766.56     450   767.4     454  767.63  600.01  768.79
#Mann= 1 ,-1 , 0
       0    .045       0
Bank Sta=280,320
XS Rating Curve= 0 ,0
Exp/Cntr=0.3,0.1

Type RM Length L Ch R = 1 ,559.9999,80,80,80
XS GIS Cut Line= 2
3111749.0491461810162381.46826793111832.9495689310161787.3631569
#Sta/Elev= 30
       0  766.92   63.95  765.61  129.39  763.21  144.88  762.23  198.34  759.39
  231.31  756.93   239.8  755.63   240.8  755.35   245.3  752.95  248.29   752.1
  254.79  751.45  256.79   750.9  261.78  750.69     280  750.67  301.25  750.59
  315.24  751.49     320  752.04  323.73  752.46  336.72  752.65   357.7  756.75
   366.7  758.13  373.19  759.35  375.19  760.04  380.18  761.21  401.67  762.23
  412.16     765  425.15  766.16  428.14  766.56  522.07  767.87     600  768.07
#Mann= 1 ,-1 , 0
       0    .045       0
Bank Sta=280,320
XS Rating Curve= 0 ,0
Exp/Cntr=0.3,0.1

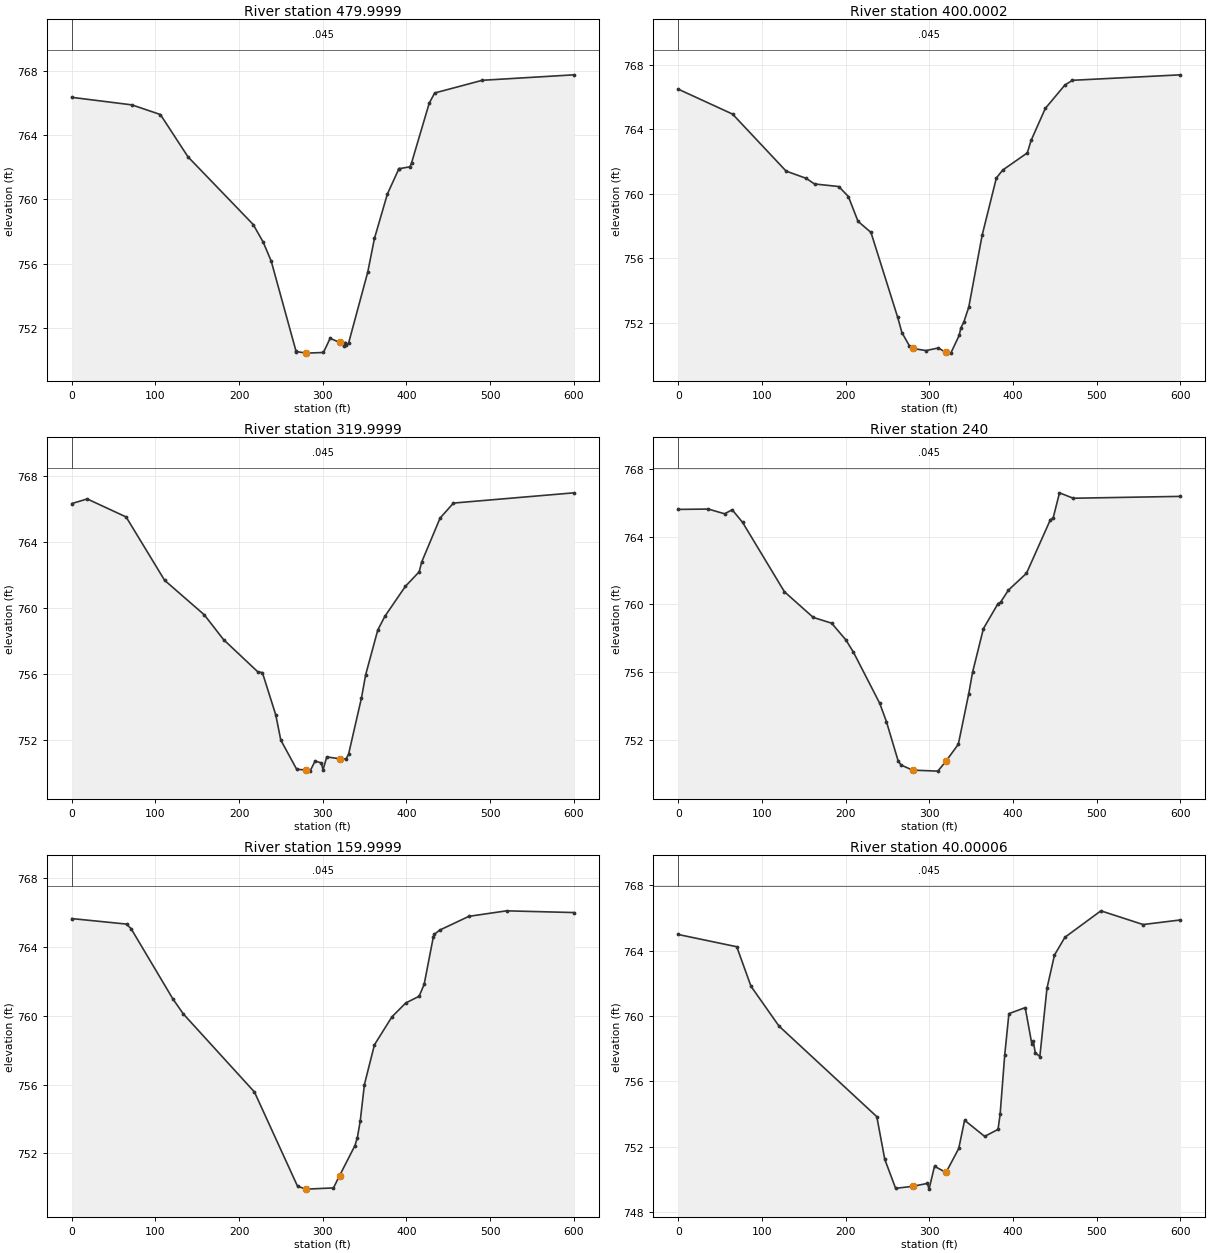
Type RM Length L Ch R = 1 ,479.9999,82.22,80,77.78
XS GIS Cut Line= 2
 3111828.263226610162392.65492533111912.1636493510161798.5498144
#Sta/Elev= 29
       0  766.34   71.94  765.87  105.91  765.27  138.88  762.64  216.82  758.43
  228.81  757.33   238.3  756.16  267.78  750.59  268.28  750.53     280  750.43
  300.75  750.47  308.74  751.35     320   751.1  324.73   750.9  326.23  751.04
  326.73  751.04  328.23  750.92  330.73  751.04  353.71  755.47   361.7  757.56
  377.19  760.33  390.68  761.87  391.18   761.9  404.16  762.02  406.16  762.28
  427.14  765.97  433.64  766.61  490.59   767.4     600  767.74
#Mann= 1 ,-1 , 0
       0    .045       0
Bank Sta=280,320
XS Rating Curve= 0 ,0
Exp/Cntr=0.3,0.1

Type RM Length L Ch R = 1 ,400.0002,80,80,80
XS GIS Cut Line= 2
 3111920.851624110162404.04565063111978.3269028410161806.8047191
#Sta/Elev= 30
       0   766.5   64.95  764.95  128.89  761.41  152.87  760.96  162.86  760.61
  191.84  760.45  203.33  759.83  214.82  758.29  230.31   757.6  262.28  752.32
  267.28  751.38  276.27  750.55     280  750.39  296.25  750.26  310.74  750.42
     320  750.14  325.73   750.1  335.72   751.2  337.72  751.66  341.22  752.02
  347.21  752.96   363.2  757.43  380.18  760.98  387.68  761.47  417.15  762.54
  421.65  763.31  438.63   765.3  462.11  766.76  471.11  767.05     600  767.39
#Mann= 1 ,-1 , 0
       0    .045       0
Bank Sta=280,320
XS Rating Curve= 0 ,0
Exp/Cntr=0.3,0.1

Type RM Length L Ch R = 1 ,319.9999,80,80,80
XS GIS Cut Line= 2
3112000.4840107610162411.70902113112057.9589614310161814.4680896
#Sta/Elev= 30
       0  766.32   18.48   766.6   64.95  765.51  110.91  761.68  158.37  759.59
  181.35  758.09  222.31  756.14  227.81  756.09   243.8  753.53  249.79  752.01
  268.78  750.24     280   750.2  284.76  750.13  290.76  750.74  298.25  750.63
  300.25  750.21  304.75  750.99     320  750.88  327.73  750.87  330.72  751.14
  346.21  754.56  351.21  755.96  365.69  758.67  374.19   759.5  398.67  761.31
  415.15  762.19  418.15  762.78  440.13  765.44  456.12  766.35     600  766.97
#Mann= 1 ,-1 , 0
       0    .045       0
Bank Sta=280,320
XS Rating Curve= 0 ,0
Exp/Cntr=0.3,0.1

Type RM Length L Ch R = 1 ,240     ,79.16,80,80.84
XS GIS Cut Line= 2
3112080.1160693510162419.37239163112137.5910200210161822.1314601
#Sta/Elev= 30
       0  765.61   35.97  765.63   55.45  765.35   64.45  765.59   76.94  764.84
  126.89  760.74  161.37  759.22  183.35  758.88  200.33  757.89  209.33  757.17
   240.8  754.14  248.79  753.06  262.78  750.74  266.28  750.49     280  750.19
  310.24  750.13     320  750.72  334.72  751.72  347.21  754.72  351.71  755.97
   364.7  758.56  382.18  760.04  385.18  760.12  394.67  760.84  416.15  761.83
  444.63  764.99  448.12  765.12  455.62  766.59   472.1  766.27     600  766.38
#Mann= 1 ,-1 , 0
       0    .045       0
Bank Sta=280,320
XS Rating Curve= 0 ,0
Exp/Cntr=0.3,0.1

Type RM Length L Ch R = 1 ,159.9999,120,120,120
XS GIS Cut Line= 2
3112154.7127049310162426.8421929 3112222.189604110161830.6485034
#Sta/Elev= 25
       0  765.64   65.45  765.32   70.94  765.05   120.9  760.97  133.39   760.1
  218.32  755.57  269.78   750.1     280  749.93  312.74     750     320  750.71
  338.22  752.44  341.22   752.9  344.71  753.88  349.71     756   361.7  758.31
  382.68  759.94  399.17  760.74  415.15  761.13  421.15  761.83  432.14  764.59
  433.14  764.72  439.63  764.97   474.6  765.77  519.56  766.09     600  765.99
#Mann= 1 ,-1 , 0
       0    .045       0
Bank Sta=280,320
XS Rating Curve= 0 ,0
Exp/Cntr=0.3,0.1

Type RM Length L Ch R = 1 ,40.00006,40,40,40
XS GIS Cut Line= 2
3112273.9513115910162440.33757283112341.4282107710161844.1438833
#Sta/Elev= 30
       0  764.99   69.94  764.24   86.93  761.82   120.4  759.38   237.3  753.83
   246.8  751.22  259.78  749.44     280  749.56  297.75  749.74  299.75  749.39
  306.25  750.79     320  750.41  335.22  751.88  342.21  753.61  366.19  752.62
  382.18  753.05  384.68  753.98  390.17  757.61  395.17  760.14  414.65  760.51
  422.65  758.26  424.14  758.48  426.64  757.75  432.14  757.51  440.63  761.69
  449.62  763.73  462.11  764.82  505.08  766.44  555.53   765.6     600  765.88
#Mann= 1 ,-1 , 0
       0    .045       0
Bank Sta=280,320
XS Rating Curve= 0 ,0
Exp/Cntr=0.3,0.1

Chan Stop Cuts=-1
Use User Specified Reach Order=0
Composite Channel Slope=5